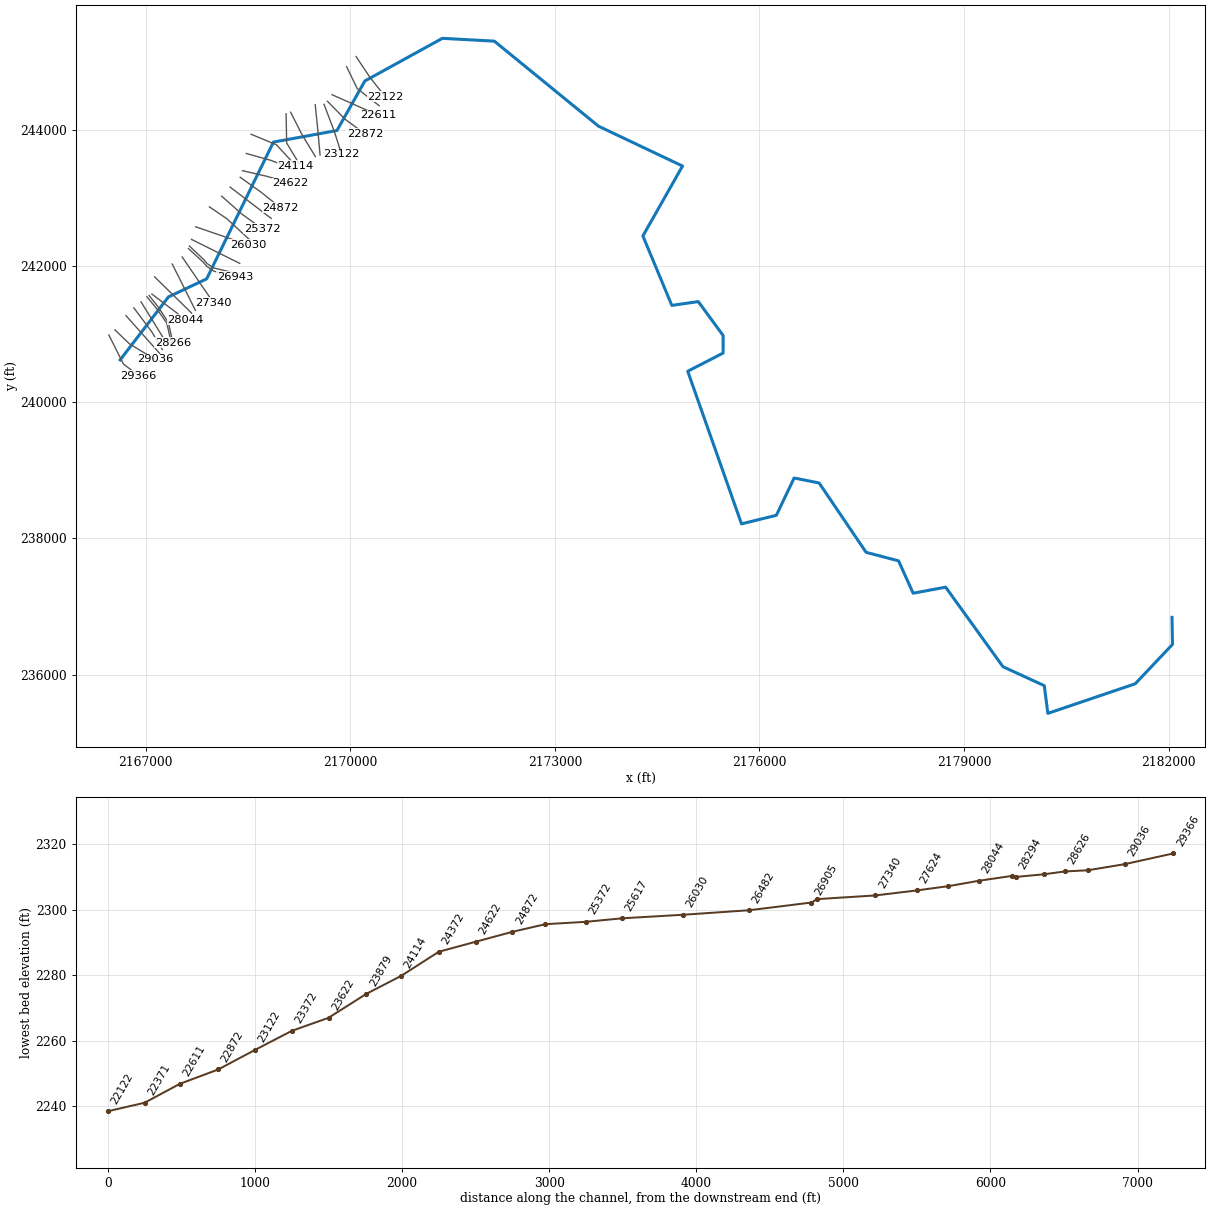
--- COVECK.prj (project) ---

Proj Title=COVECK
Current Plan=p01
Default Exp/Contr=0,0
English Units
Geom File=g01
Flow File=f01
Plan File=p01
Background Map Layer=Inundation Boundary (01pct Value_0)
BEGIN DESCRIPTION:
Stream Name: Cove Creek
Flood Zone:Approximate
Monroe County, West Virginia
HEC-RAS Version: 5.0.7
Vertical Datum: NAVD88
Projection: NAD 1983 StatePlane West Virginia S FIPS 4702 (US Feet)
LiDAR: 2016, 1-meter
Land Use: 2016 NLCD
Hydrologic Method:
Regression
Model Notes:
Model extends beyond county boundary into Allegany county.
END DESCRIPTION:
DSS Export Rating Curves= 0
DSS Export Rating Curve Sorted= 0
DSS Export Volume Flow Curves= 0
DXF OffsetX= 0
DXF OffsetY= 0
DXF ScaleX= 0
DXF ScaleY= 0

--- COVECK.p01 (plan) ---

Plan Title=Floodplain
Program Version=5.07
Short Identifier=Floodplain
Geom File=g01
Flow File=f01
Subcritical Flow
K Sum by GR= 0
Std Step Tol= 0.01
Critical Tol= 0.01
Num of Std Step Trials= 20
Max Error Tol= 0.3
Flow Tol Ratio= 0.001
Split Flow NTrial= 30
Split Flow Tol= 0.02
Split Flow Ratio= 0.02
Log Output Level= 0
Friction Slope Method= 1
Unsteady Friction Slope Method= 2
Unsteady Bridges Friction Slope Method= 1
Parabolic Critical Depth
Global Vel Dist= 0 , 0 , 0
Global Log Level= 0
CheckData=True
Encroach Param=-1 ,0,0, 0
Mapping Interval=1HOUR
Computation Time Step Use Courant=        0
Computation Time Step Use Time Series=    0
Computation Time Step Count To Double=0
Computation Time Step Max Doubling=0
Computation Time Step Max Halving=0
Computation Time Step Residence Courant=0
Run HTab= 0
Run UNet= 0
Run Sediment= 0
Run PostProcess= 0
Run WQNet= 0
Run RASMapper=-1
UNET Theta= 0
UNET Theta Warmup= 0
UNET ZTol= 0
UNET ZSATol= 0
UNET MxIter= 0
UNET Max Iter WO Improvement= 0
UNET MaxInSteps= 0
UNET DtIC= 0
UNET DtMin= 0
UNET MaxCRTS= 0
UNET WFStab= 0
UNET SFStab= 0
UNET WFX= 1
UNET SFX= 1
UNET 1D Methodology=Finite Difference
UNET DSS MLevel= 1
UNET Pardiso=0
UNET DZMax Abort= 0
UNET Use Existing IB Tables= 0
UNET Froude Reduction=False
UNET Froude Limit= 0
UNET Froude Power= 0
UNET D1 Cores= 0
UNET D2 Coriolis=0
UNET D2 Cores= 0
UNET D2 Theta= 1
UNET D2 Theta Warmup= 1
UNET D2 Z Tol= 0.01
UNET D2 Volume Tol= 0.01
UNET D2 Max Iterations= 20
UNET D2 Equation= 0
UNET D2 RampUpFraction=0.1
UNET D2 TimeSlices= 1
UNET D2 BCVolumeCheck=0
UNET D1D2 MaxIter= 0
UNET D1D2 ZTol=0.01
UNET D1D2 QTol=0.1
UNET D1D2 MinQTol=1
Write IC File= 0
Write IC File at Fixed DateTime=0
Write IC File at Sim End=0
Echo Input=False
Echo Parameters=False
Echo Output=False
Write Detailed= 0
HDF Write Warmup=0
HDF Write Time Slices=0
HDF Flush=0
HDF Face Node Velocities=0
HDF Compression= 1
HDF Chunk Size= 1
HDF Spatial Parts= 1
HDF Use Max Rows=0
HDF Fixed Rows= 1
Calibration Method= 0
Calibration Iterations= 20
Calibration Max Change=0.05
Calibration Tolerance=0.2
Calibration Maximum=1.5
Calibration Minimum=0.5
Calibration Optimization Method= 1
WQ AD Non Conservative
WQ ULTIMATE=-1
WQ Max Comp Step=1HOUR
WQ Output Interval=15MIN
WQ Output Selected Increments= 0
WQ Output face flow=0
WQ Output face velocity=0
WQ Output face area=0
WQ Output face dispersion=0
WQ Output cell volume=0
WQ Output cell surface area=0
WQ Output cell continuity=0
WQ Output cumulative cell continuity=0
WQ Output face conc=0
WQ Output face dconc_dx=0
WQ Output face courant=0
WQ Output face peclet=0
WQ Output face adv mass=0
WQ Output face disp mass=0
WQ Output cell mass=0
WQ Output cell source sink temp=0
WQ Output nsm pathways=0
WQ Output nsm derived pathways=0
WQ Output MaxMinRange=-1
WQ Daily Max Min Mean=-1
WQ Daily Range=0
WQ Daily Time=0
WQ Create Restart=0
WQ Fixed Restart=0
WQ System Summary=0
WQ Write To DSS=0
WQ Use Fixed Temperature=0
Sorting and Armoring Iterations= 10
XS Update Threshold= 0.02
Bed Roughness Predictor= 0
Hydraulics Update Threshold= 0.02
Energy Slope Method= 1
Volume Change Method= 1
Sediment Retention Method= 0
XS Weighting Method= 0
Number of US Weighted Cross Sections= 1
Number of DS Weighted Cross Sections= 1
Upstream XS Weight=0
Main XS Weight=1
Downstream XS Weight=0
Number of DS XS's Weighted with US Boundary= 1
Upstream Boundary Weight= 1
Weight of XSs Associated with US Boundary= 0
Number of US XS's Weighted with DS Boundary= 1
Downstream Boundary Weight= 0.5
Weight of XSs Associated with DS Boundary= 0.5
Percentile Method= 0
Sediment Output Level= 3
Mass or Volume Output= 0
Output Increment Type= 1
Profile and TS Output Increment= 1
XS Output Flag= 0
XS Output Increment= 10
Write Gradation File= 0
Read Gradation Hotstart= 0
Write HDF5 File= 1
Write Binary Output= 1
Write DSS Sediment File= 0
SV Curve= 0
Specific Gage Flag= 0

--- COVECK.f01 (steady flow) ---

Flow Title=Flow
Program Version=5.07
Number of Profiles= 6
Profile Names=01pct,10pct,04pct,02pct,0_2pct,01plus
River Rch & RM=COVECK,Main            ,29366
     697     371     492     591     970    1030
River Rch & RM=COVECK,Main            ,27834
     775     414     548     658    1080    1150
River Rch & RM=COVECK,Main            ,27340
     836     448     592     710    1160    1240
River Rch & RM=COVECK,Main            ,26030
     875     470     620     743    1210    1290
River Rch & RM=COVECK,Main            ,24872
    1030     557     733     877    1420    1520
River Rch & RM=COVECK,Main            ,24372
    1060     576     757     905    1470    1570
River Rch & RM=COVECK,Main            ,22611
    1170     638     837    1000    1620    1740
River Rch & RM=COVECK,Main            ,20872
    1290     705     923    1100    1780    1910
River Rch & RM=COVECK,Main            ,20372
    1708     942    1227    1460    2337    2526
River Rch & RM=COVECK,Main            ,19872
    1830    1010    1320    1570    2500    2710
River Rch & RM=COVECK,Main            ,15367
    2030    1120    1460    1730    2760    3000
River Rch & RM=COVECK,Main            ,9872
    2150    1200    1550    1840    2930    3180
River Rch & RM=COVECK,Main            ,2680
    3370    1910    2450    2890    4550    4980
Boundary for River Rch & Prof#=COVECK,Main            , 1
Up Type= 0
Dn Type= 3
Dn Slope=0.0077
Boundary for River Rch & Prof#=COVECK,Main            , 2
Up Type= 0
Dn Type= 3
Dn Slope=0.0077
Boundary for River Rch & Prof#=COVECK,Main            , 3
Up Type= 0
Dn Type= 3
Dn Slope=0.0077
Boundary for River Rch & Prof#=COVECK,Main            , 4
Up Type= 0
Dn Type= 3
Dn Slope=0.0077
Boundary for River Rch & Prof#=COVECK,Main            , 5
Up Type= 0
Dn Type= 3
Dn Slope=0.0077
Boundary for River Rch & Prof#=COVECK,Main            , 6
Up Type= 0
Dn Type= 3
Dn Slope=0.0077
DSS Import GetInterval= 0
DSS Import GetPeak= 0
DSS Import FillOption= 0

--- COVECK.g01 (geometry) ---

Geom Title=Geometry
Program Version=5.07

River Reach=COVECK          ,Main
Reach XY= 30
     2166623.512      240619.327     2167332.063      241543.806
     2167891.958      241808.563     2168871.776      243815.941
     2169802.766      243985.212     2170211.837      244712.208
      2171348.99      245338.294     2172110.708      245297.061
     2173639.277      244048.762     2174871.048      243464.126
     2174289.885      242438.302     2174714.147      241419.421
     2175102.602       241474.76     2175467.185      240976.713
       2175466.1      240719.552     2174947.437      240452.625
     2175736.283      238213.041      2176247.35       238338.91
     2176507.767      238885.784     2176874.521      238813.085
     2177563.539       237795.29       2178038.8      237670.507
     2178253.644      237195.246     2178729.989      237284.222
     2179570.918      236116.687     2180176.387      235838.909
     2180229.083      235431.968      2181510.89      235866.738
      2182056.68      236443.995      2182050.17       236841.13

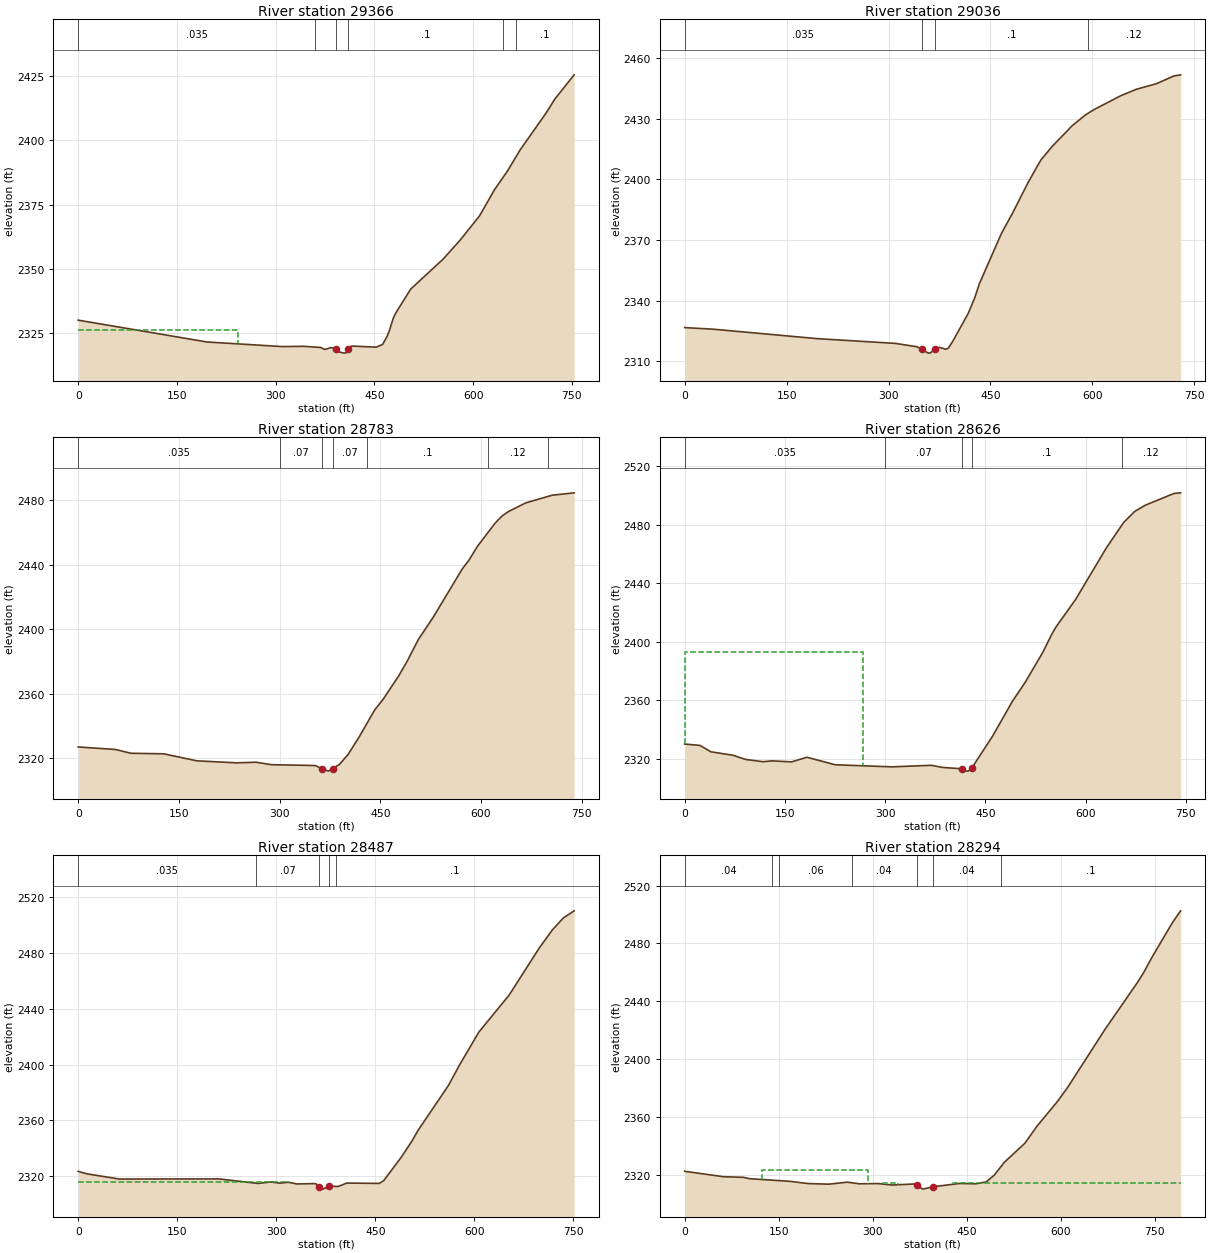
Type RM Length L Ch R = 1 ,29366   ,330.1,330.1,330.1
XS GIS Cut Line= 3
     2166457.782      240984.502     2166671.219      240559.321
     2166891.433      240389.926
#Sta/Elev= 30
       0  2330.1   195.5 2321.61   309.6 2319.82   342.2 2319.92   368.2 2319.48
   374.7 2318.69   384.5 2319.45     391 2318.87   397.5 2317.66   404.1 2317.27
   407.3 2317.44   410.6 2318.81   413.8 2319.86   417.1 2320.01   452.9  2319.6
   462.7 2320.69   469.2 2323.73   472.5 2325.78     479 2331.04   482.3 2332.77
   505.2 2342.18   554.2 2353.76   580.3 2361.22   609.8 2370.66   632.6 2380.86
   652.2 2388.09   671.9 2396.48   711.1 2410.73   724.2 2416.11   753.6 2425.55
#Mann= 6 ,-1 , 0
       0    .035       0     360      .1       0     391    .045       0
   410.6      .1       0  645.75     .12       0  665.75      .1       0
#XS Ineff= 2 , 0
          242.23  2326.1
Permanent Ineff=
       F       F
Bank Sta=391,410.6
XS Rating Curve= 0 ,0
Exp/Cntr=0.3,0.1

Type RM Length L Ch R = 1 ,29036   ,252.6,252.4,243.2
XS GIS Cut Line= 3
     2166547.561      241059.036     2166759.305      240855.762
     2167131.973      240628.773
#Sta/Elev= 30
       0 2326.63    42.4 2325.82   195.7 2321.14   309.8 2318.82   342.4 2317.12
   348.8 2315.85   358.6 2313.99   361.9 2314.13   368.4 2316.27   374.9 2316.82
   384.7  2315.9     388 2316.48   394.5 2319.79   417.3 2333.65     427 2341.42
   433.6 2348.24   466.1 2373.17   482.4 2383.17   505.2 2398.27   521.5 2408.02
   524.7 2409.78     541 2416.32   570.3 2426.54   589.8 2431.87   602.9  2434.6
     642 2441.41   664.8 2444.57   694.1 2447.31   720.1 2451.17   729.9 2451.72
#Mann= 4 ,-1 , 0
       0    .035       0   348.8    .045       0   368.4      .1       0
  593.52     .12       0
Bank Sta=348.8,368.4
XS Rating Curve= 0 ,0
Exp/Cntr=0.3,0.1

Type RM Length L Ch R = 1 ,28783   ,155.2,157.1,153.2
XS GIS Cut Line= 2
     2166709.129      241268.413     2167200.728      240716.994
#Sta/Elev= 30
       0  2327.1    55.6 2325.54    78.4 2323.19   127.5 2322.84   176.5 2318.51
   235.4 2317.25   264.8 2317.63   287.6 2316.11     353 2315.58   363.8  2313.5
   372.6 2312.11   378.8 2313.73     389 2316.22   402.1  2322.5   418.4 2333.28
   441.3 2349.87   454.4 2356.81   477.2 2371.06   490.3 2380.53   506.7  2393.8
   529.5 2408.03     572 2437.52   581.8 2442.82   594.9  2451.7   621.1 2465.98
   630.9 2470.23   640.7  2473.1   666.8 2478.53     706 2483.26   738.7 2484.74
#Mann= 7 ,-1 , 0
       0    .035       0     300     .07       0   363.8    .045       0
   378.8     .07       0     430      .1       0     610     .12       0
     700      .1       0
Bank Sta=363.8,378.8
XS Rating Curve= 0 ,0
Exp/Cntr=0.3,0.1

Type RM Length L Ch R = 1 ,28626   ,139.4,139.1,133.9
XS GIS Cut Line= 3
     2166824.426      241382.359     2167084.843      241034.703
     2167242.395       240770.38
#Sta/Elev= 30
       0 2330.23    22.9  2329.3    39.2 2324.94    71.8 2322.63    91.4  2319.7
   117.6 2318.16   130.6 2318.75     160 2318.05   182.9 2321.21   225.4 2316.08
   310.3 2314.66   369.1 2315.72   385.4 2314.28   414.8 2313.34   421.3 2311.74
   424.6 2311.81   429.9 2314.05   460.6 2335.53     490 2359.08   509.7 2372.49
   535.9 2392.84     549 2404.92   555.5 2410.06     585 2428.94   630.8 2463.99
     657 2481.59   673.4 2489.02   689.7 2493.36   732.3  2501.3   742.1 2501.72
#Mann= 5 ,-1 , 0
       0    .035       0     300     .07       0   414.8    .045       0
   429.9      .1       0  654.38     .12       0
#XS Ineff= 2 , 0
          266.33 2392.79
Permanent Ineff=
       F       F
Bank Sta=414.8,429.9
XS Rating Curve= 0 ,0
Exp/Cntr=0.3,0.1

Type RM Length L Ch R = 1 ,28487   ,188.1,192.8,183.7
XS GIS Cut Line= 2
     2166929.895      241470.901     2167324.426      240831.578
#Sta/Elev= 30
       0  2323.6    13.1 2321.83    62.3  2318.1   213.2  2318.2   272.3 2314.96
     292 2316.03   305.1 2315.12   318.2 2315.81   331.3 2314.59   357.6 2314.84
   360.9 2314.52   364.2 2312.64   367.4 2311.22   370.7 2310.89   380.6 2313.07
   393.7 2312.76   406.8 2315.23     456 2314.97   462.6 2316.87   488.8 2333.32
   505.2 2344.98     515 2353.03     561  2385.1   577.4 2399.47   606.9 2423.16
   652.8 2449.64   698.8 2483.57   718.4  2496.3   734.9  2504.8   751.3  2509.9
#Mann= 5 ,-1 , 0
       0    .035       0     270     .07       0   364.2    .045       0
   380.6     .07       0     390      .1       0
#XS Ineff= 2 , 0
          319.25 2315.94
Permanent Ineff=
       F       F
Bank Sta=364.2,380.6
XS Rating Curve= 0 ,0
Exp/Cntr=0.5,0.3

Type RM Length L Ch R = 1 ,28294   ,28.4,28.4,28.4
XS GIS Cut Line= 4
     2167017.135      241545.119     2167160.364      241369.338
     2167307.499      241158.401     2167375.208      240858.922
#Sta/Elev= 30
       0 2322.41    61.6 2318.66    93.9 2318.22   103.7 2317.28   168.4 2315.44
   197.6  2313.9     230  2313.5   259.3 2314.89   278.8 2313.75   308.1 2313.92
   330.9 2312.91   366.7 2313.64     370  2312.9   379.8 2310.07     396 2311.72
   438.4 2313.98   464.4 2313.76   480.7 2315.03   493.7 2319.71   510.1 2328.75
   542.7 2341.82   562.3  2353.8     595 2370.92   611.3 2380.71   670.1 2420.33
   722.4 2453.11   732.2 2459.88   745.2  2470.3   777.9 2494.32     791  2502.5
#Mann= 7 ,-1 , 0
       0     .04       0     140    .035       0     150     .06       0
  266.75     .04       0     370    .045       0     396     .04       0
  503.93      .1       0
#XS Ineff= 3 ,-1
  123.16  291.962323.535     317  339.97    2314   428.4  799.732314.055
Permanent Ineff=
       F       F       F
Bank Sta=370,396
XS Rating Curve= 0 ,0
Exp/Cntr=0.5,0.3

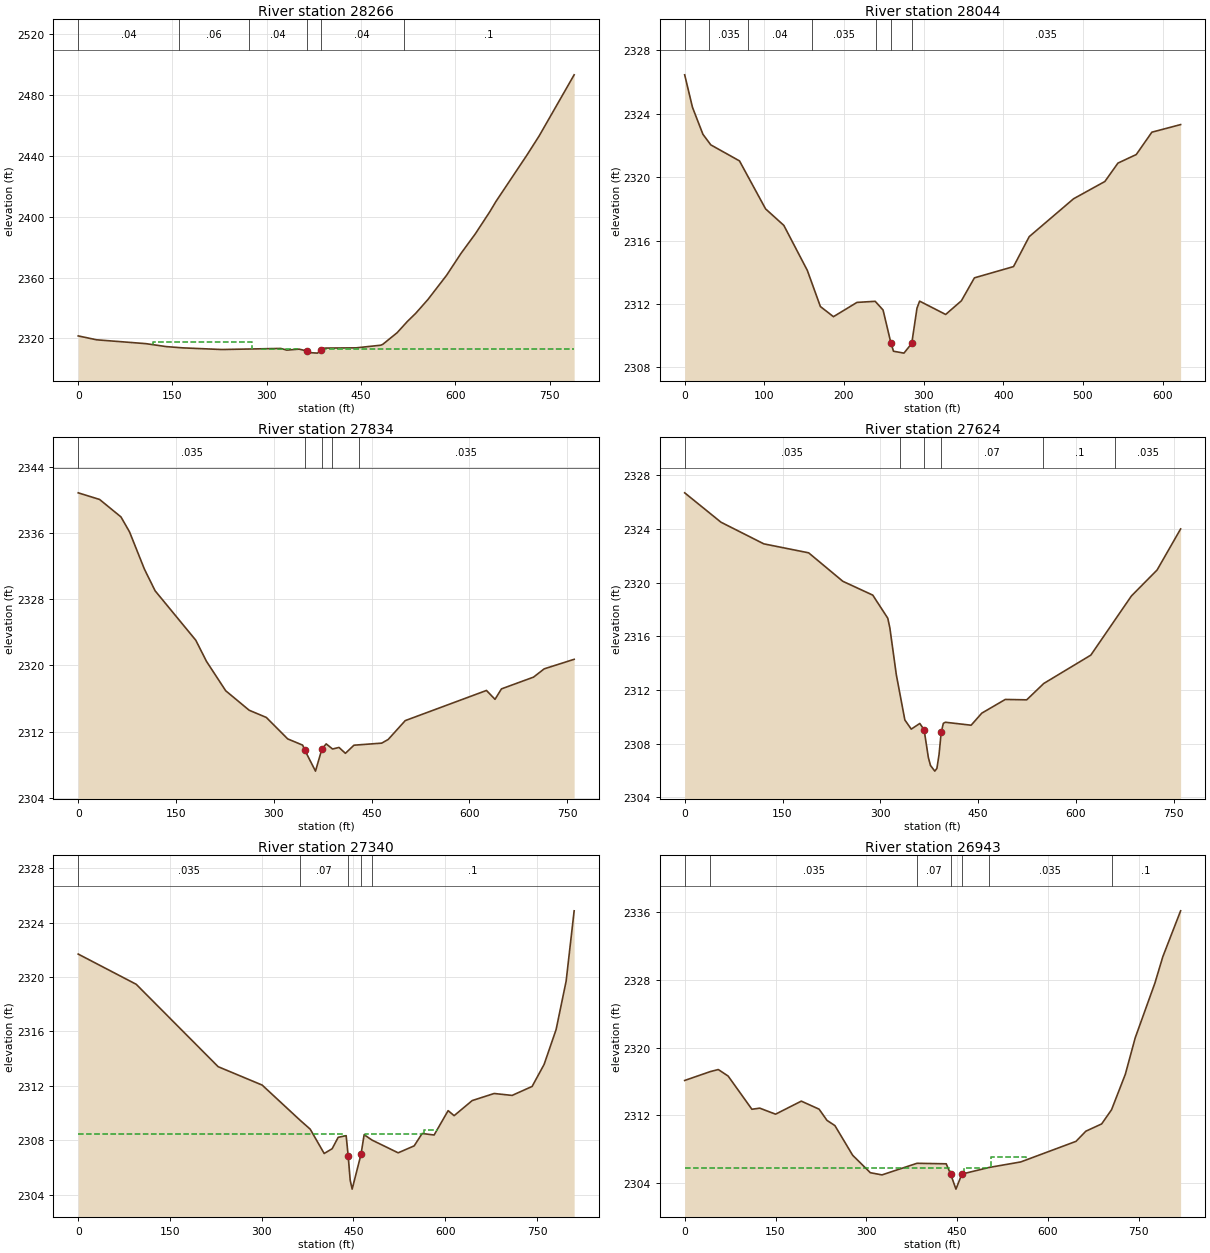
Type RM Length L Ch R = 1 ,28266   ,216,222.4,223.9
XS GIS Cut Line= 4
     2167048.385      241564.651     2167185.103      241390.172
     2167330.937      241167.515     2167396.041      240873.244
#Sta/Elev= 30
       0 2321.68    29.3 2319.12   107.6  2316.6   140.2 2314.65   166.2 2313.83
   228.2 2312.74   322.3 2313.45     332 2312.35   351.5 2312.99   364.5 2311.72
     371 2310.63   380.7 2310.37  385.83 2312.14   390.4 2313.54   393.7 2313.69
   442.4 2313.84   481.3 2315.56   484.6 2316.12   507.5 2323.78   523.9 2331.21
     537 2336.47   556.6 2345.63   586.1 2361.43     609 2375.77     632 2388.76
   654.9 2403.18   664.7 2409.93   713.9 2440.34   733.5    2453   789.2 2493.14
#Mann= 6 ,-1 , 0
       0     .04       0     160     .06       0  271.66     .04       0
   364.5    .045       0  385.83     .04       0  517.83      .1       0
#XS Ineff= 3 ,-1
  118.57  276.76 2317.87  291.57  349.46 2313.24  387.82   789.2 2313.28
Permanent Ineff=
       F       F       F
Bank Sta=364.5,385.83
XS Rating Curve= 0 ,0
Exp/Cntr=0.5,0.3

Type RM Length L Ch R = 1 ,28044   ,203.9,209.5,200.5
XS GIS Cut Line= 2
     2167088.749      241585.484     2167584.843      241209.182
#Sta/Elev= 30
       0 2326.46     9.8 2324.41    22.9 2322.71    32.8 2322.04    68.8 2321.03
   101.6    2318   124.5 2316.96     154 2314.12   170.4 2311.84   186.8  2311.2
   216.3  2312.1   239.2 2312.17   249.1 2311.62   258.9 2309.55   262.2 2309.02
   275.3  2308.9   285.1 2309.51   291.7 2311.74     295 2312.18   327.7 2311.34
   347.4  2312.2   363.8 2313.65   412.9 2314.36   432.6 2316.25   488.3 2318.64
   527.6 2319.73     544 2320.89     567 2321.43   586.6 2322.84   622.7 2323.32
#Mann= 7 ,-1 , 0
       0     .04       0      30    .035       0      80     .04       0
     160    .035       0     240     .04       0   258.9    .045       0
   285.1    .035       0
Bank Sta=258.9,285.1
XS Rating Curve= 0 ,0
Exp/Cntr=0.3,0.1

Type RM Length L Ch R = 1 ,27834   ,214.4,209.9,199.5
XS GIS Cut Line= 2
     2167128.145      241837.969     2167671.849      241305.844
#Sta/Elev= 30
       0 2340.84    32.8 2340.04    65.6 2337.93    78.7 2336.13   101.6 2331.62
     118 2329.01   180.4 2323.04   196.8 2320.49   226.3 2316.94   262.3 2314.59
   288.6 2313.72   321.4 2311.13   344.3 2310.38   347.6 2309.77     364 2307.24
   373.8  2309.9   380.4 2310.53   390.2 2309.91   400.1  2310.1   409.9 2309.39
     423 2310.37   465.6 2310.62   475.5 2311.06   501.7 2313.34   626.3 2316.98
   639.4 2315.91   649.3 2317.17   698.5 2318.59   714.9 2319.59   760.8 2320.74
#Mann= 5 ,-1 , 0
       0    .035       0   347.6    .045       0   373.8    .035       0
     390     .07       0     430    .035       0
Bank Sta=347.6,373.8
XS Rating Curve= 0 ,0
Exp/Cntr=0.3,0.1

Type RM Length L Ch R = 1 ,27624   ,276,284,286.1
XS GIS Cut Line= 2
     2167386.926       242026.89     2167727.045       241346.82
#Sta/Elev= 30
       0 2326.69    55.7  2324.5   121.3 2322.89   190.1 2322.22   242.5  2320.1
   288.4 2319.07   311.4 2317.35   314.6 2316.63   324.5 2313.14   337.6 2309.77
   347.4 2309.09   360.5 2309.51   367.1 2309.04   373.6 2306.98   376.9 2306.38
   383.5 2305.96   386.7 2306.16     390 2307.19   393.3 2308.84   396.6 2309.52
   399.8  2309.6   439.2 2309.38   455.6 2310.28   491.6  2311.3   524.4 2311.27
   550.6 2312.49   622.7  2314.6     685 2319.01   724.3 2320.94   760.4    2324
#Mann= 6 ,-1 , 0
       0    .035       0     330     .07       0   367.1    .045       0
   393.3     .07       0     550      .1       0     660    .035       0
Bank Sta=367.1,393.3
XS Rating Curve= 0 ,0
Exp/Cntr=0.3,0.1

Type RM Length L Ch R = 1 ,27340   ,343.7,397.5,386.5
XS GIS Cut Line= 2
      2167532.76      242129.755     2167990.367      241460.585
#Sta/Elev= 30
       0 2321.69    94.8 2319.47   228.8 2313.41   300.7 2312.06   362.8 2309.47
   379.2 2308.82   402.1 2307.03   415.1 2307.38     425 2308.22     438 2308.34
   441.3 2306.87   444.6 2305.07   447.8 2304.41  462.25 2306.96   467.4 2308.41
   480.5 2308.01     523 2307.08   549.2 2307.59   562.2  2308.5   581.8 2308.39
   604.7 2310.18   614.5 2309.81     644 2310.92   679.9 2311.44   709.3  2311.3
     742 2311.96   761.6 2313.58   781.2 2316.14   797.6  2319.7   810.7 2324.87
#Mann= 5 ,-1 , 0
       0    .035       0   362.8     .07       0   441.3    .045       0
  462.25     .07       0   480.5      .1       0
#XS Ineff= 3 ,-1
       0  434.65 2308.48  469.32     564 2308.46  564.51  585.92 2308.79
Permanent Ineff=
       F       F       F
Bank Sta=441.3,462.25
XS Rating Curve= 0 ,0
Exp/Cntr=0.5,0.3

Type RM Length L Ch R = 1 ,26943   ,37.6,37.6,37.6
XS GIS Cut Line= 5
     2167626.307        242252.1     2167844.623      242050.711
     2167891.932      241994.288     2168001.307      241920.069
     2168307.297      241840.642
#Sta/Elev= 30
       0 2316.11    42.4 2317.16    55.5  2317.4    71.8 2316.63     111 2312.71
     124 2312.84   150.1 2312.13   192.6 2313.67     222 2312.72     235  2311.4
   248.1 2310.78   277.4 2307.28   306.6 2305.22   325.8 2304.96   383.6 2306.33
   431.9 2306.27  439.18 2305.06     448 2303.28  457.792305.059   502.8 2305.84
     555 2306.49   646.2 2308.92   662.5 2310.12   688.6 2310.98   704.9 2312.65
   727.7 2316.84     744 2321.14   776.6 2327.62   789.6 2330.72     819 2336.14
#Mann= 7 ,-1 , 0
       0     .04       0    42.4    .035       0   383.6     .07       0
  439.18    .045       0  457.79     .07       0   502.8    .035       0
   704.9      .1       0
#XS Ineff= 3 ,-1
       0   438.2  2305.8   460.9     505  2305.8  505.08  564.41 2307.11
Permanent Ineff=
       F       F       F
Bank Sta=439.18,457.79
XS Rating Curve= 0 ,0
Exp/Cntr=0.5,0.3

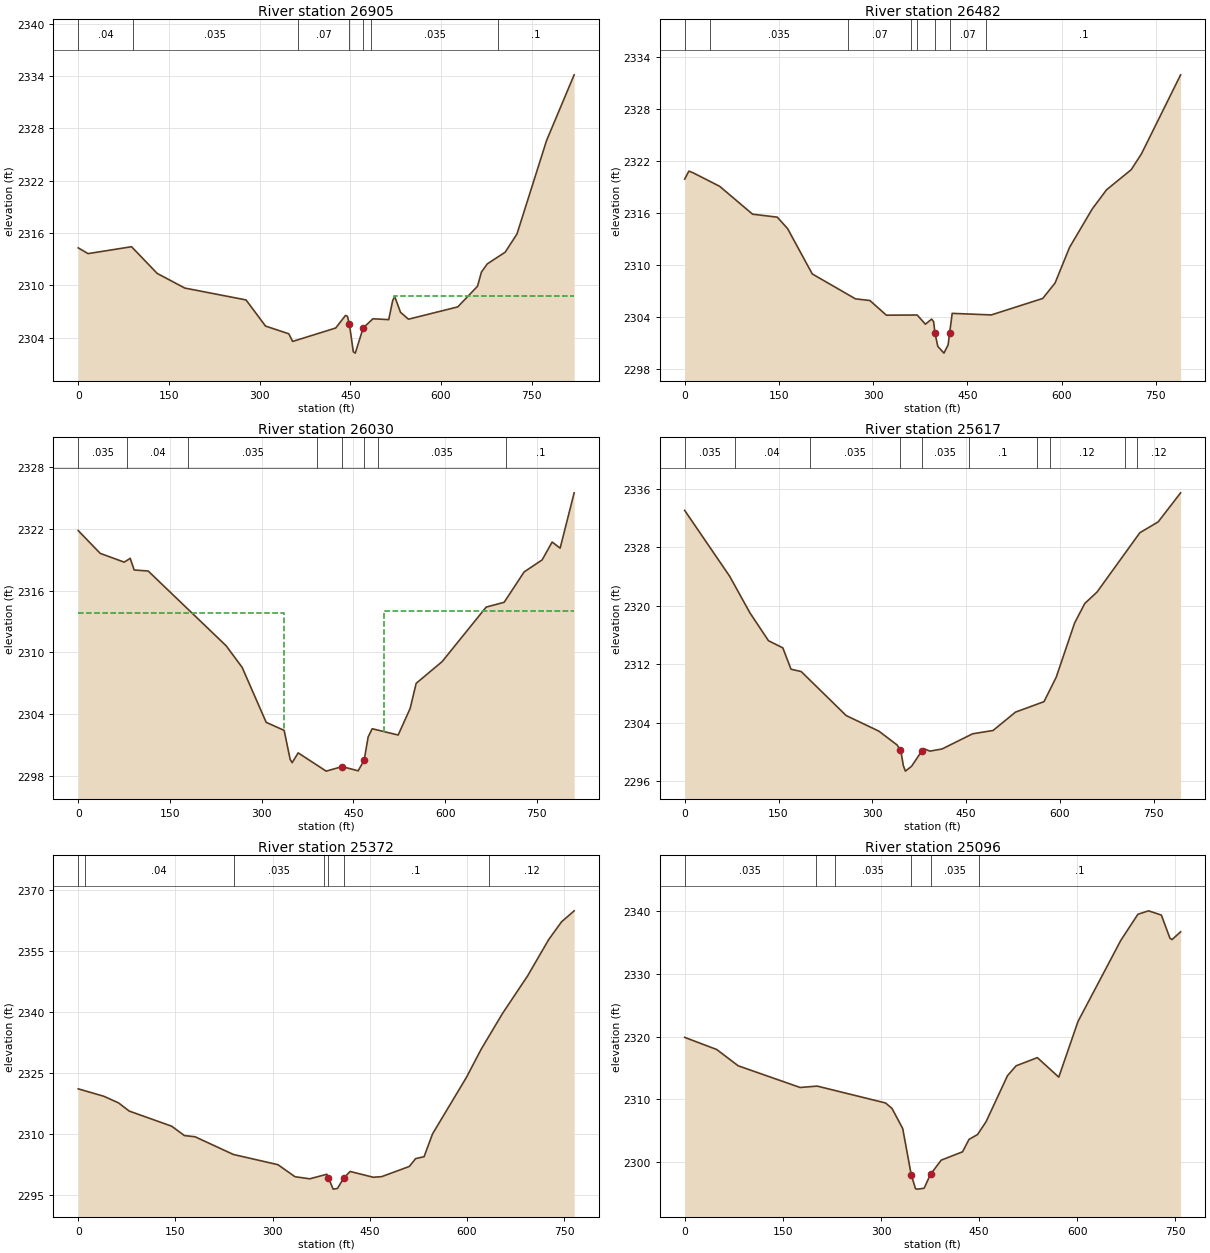
Type RM Length L Ch R = 1 ,26905   ,423,423,423
XS GIS Cut Line= 5
     2167638.894      242290.294     2167852.436      242088.472
     2167899.745      242032.048     2167997.401      241968.246
     2168324.224      241890.121
#Sta/Elev= 30
       0 2314.31    16.3 2313.65    88.2 2314.44   130.6 2311.38   176.3  2309.7
   277.5 2308.34   309.8 2305.34   348.2 2304.46   354.6 2303.58   425.8 2305.12
     442 2306.56   445.2 2306.47   448.5 2305.55   454.9  2302.4   458.2 2302.24
   471.2 2305.13   487.4 2306.18   513.5 2306.08     520 2308.26   523.3 2308.75
     533 2306.92   546.1 2306.13   627.6 2307.54   660.3 2309.91   666.8 2311.54
   676.6 2312.48     706 2313.81   725.5 2315.89   774.5 2326.62   820.1 2334.15
#Mann= 7 ,-1 , 0
       0     .04       0      90    .035       0  363.82     .07       0
   448.5    .045       0   471.2     .07       0  484.11    .035       0
  694.11      .1       0
#XS Ineff= 2 , 0
                          522.07         2308.84
Permanent Ineff=
       F       F
Bank Sta=448.5,471.2
XS Rating Curve= 0 ,0
Exp/Cntr=0.5,0.3

Type RM Length L Ch R = 1 ,26482   ,440.5,452.4,409.6
XS GIS Cut Line= 2
     2167669.824      242387.805      2168376.51      242036.005
#Sta/Elev= 30
       0 2319.92     6.6 2320.84    13.1 2320.66    55.7 2319.09   108.1 2315.88
   147.4 2315.54   163.8 2314.22   203.1    2309   271.9 2306.13   294.8 2305.94
     321 2304.25   370.1 2304.27   383.2 2303.21   393.1  2303.8   396.3 2303.49
  398.39 2302.21   402.9 2300.66   412.7 2299.88   419.3 2300.83  421.83 2302.25
   425.8 2304.46   488.1 2304.28     570 2306.18   589.6 2307.96   612.5 2312.04
   648.6 2316.47   671.5 2318.69   710.8 2321.01   727.2 2322.85   789.4 2331.93
#Mann= 8 ,-1 , 0
       0     .04       0      40    .035       0     260     .07       0
     360    .035       0     370     .07       0  398.39    .045       0
  421.83     .07       0     480      .1       0
Bank Sta=398.39,421.83
XS Rating Curve= 0 ,0
Exp/Cntr=0.3,0.1

Type RM Length L Ch R = 1 ,26030   ,409.8,412.3,356.3
XS GIS Cut Line= 2
     2167730.676      242572.463     2168497.603      242309.442
#Sta/Elev= 30
       0 2321.81      36  2319.6    75.2 2318.75      85 2319.12    91.5 2317.99
   114.4 2317.89   241.9 2310.64   268.1 2308.54   307.3 2303.22   336.7 2302.44
   346.5 2299.63   349.8 2299.31   359.6 2300.26   405.4 2298.49   431.5 2298.93
   457.7 2298.52   467.5 2299.55     474  2301.8   480.6  2302.6   523.1 2301.99
   542.7 2304.57   552.5    2307     595 2309.11   666.9 2314.39   696.4 2314.86
     729  2317.8   758.5 2318.97   774.8  2320.7   787.9 2320.11   810.8 2325.47
#Mann= 8 ,-1 , 0
       0    .035       0      80     .04       0     180    .035       0
     390     .07       0   431.5    .045       0   467.5     .07       0
     490    .035       0     700      .1       0
#XS Ineff= 2 , 0
           336.7 2313.79  499.37         2314.02
Permanent Ineff=
       F       F
Bank Sta=431.5,467.5
XS Rating Curve= 0 ,0
Exp/Cntr=0.3,0.1

Type RM Length L Ch R = 1 ,25617   ,244.6,245.6,235
XS GIS Cut Line= 3
     2167932.468      242865.249     2168191.614      242688.349
     2168543.176      242362.828
#Sta/Elev= 30
       0 2333.02    71.9 2324.03   104.6 2318.99     134 2315.22   156.9 2314.25
     170 2311.33   186.3 2311.01   258.2    2305   310.5 2302.87   339.8 2300.97
   344.4  2300.3   346.4  2299.8   349.6 2298.16   352.9 2297.41   362.7 2298.07
     379 2300.14   382.2 2300.49     392 2300.14   411.6 2300.44   460.4 2302.51
     493 2302.96   528.9 2305.47   574.5  2306.9   594.1 2310.26   623.4 2317.64
   639.7 2320.31   659.3 2321.87   727.7 2329.97     757 2331.45   792.9 2335.42
#Mann= 10 ,-1 , 0
       0    .035       0      80     .04       0     200    .035       0
   344.4    .045       0     379    .035       0  453.77      .1       0
  563.77    .035       0  583.77     .12       0  703.77      .1       0
  723.77     .12       0
Bank Sta=344.4,379
XS Rating Curve= 0 ,0
Exp/Cntr=0.3,0.1

Type RM Length L Ch R = 1 ,25372   ,269.8,275.4,266.7
XS GIS Cut Line= 3
     2168111.572      243022.181      2168406.31      242761.317
     2168707.518      242543.022
#Sta/Elev= 30
       0 2321.03    39.4 2319.21    62.3 2317.57    78.7 2315.56   144.3 2311.83
     164 2309.52   180.4 2309.23   239.4 2304.88   308.3 2302.36   334.6  2299.4
   357.5 2298.88   383.8    2300   386.1 2299.17   393.6 2296.34   400.1 2296.49
   409.9 2299.05   419.7 2300.69   455.6 2299.26   468.6 2299.42   511.1 2301.92
   520.9 2303.85   533.9 2304.32     547 2309.94   599.2 2323.82     622 2330.76
   654.6 2339.48   693.8 2348.85   726.4  2357.8     746 2362.12   765.6 2364.85
#Mann= 7 ,-1 , 0
       0      .1       0      10     .04       0     240    .035       0
     380      .1       0   386.1    .045       0   409.9      .1       0
   633.6     .12       0
Bank Sta=386.1,409.9
XS Rating Curve= 0 ,0
Exp/Cntr=0.3,0.1

Type RM Length L Ch R = 1 ,25096   ,224.1,224.6,223.8
XS GIS Cut Line= 2
     2168235.751      243155.313     2168838.749      242696.161
#Sta/Elev= 30
       0 2319.87      49 2317.93    81.7 2315.33   176.4 2311.86   202.5 2312.08
   307.1 2309.38   316.9  2308.5   333.2  2305.3   346.3 2297.87   352.8 2295.67
   356.1 2295.61   365.9 2295.75   375.7 2297.98     392 2300.24   424.7 2301.58
   434.5 2303.56   447.6 2304.34   460.6 2306.39   493.3 2313.74   506.4 2315.32
     539 2316.63   571.7 2313.51   601.1 2322.42   666.4 2335.36   692.6 2339.55
   708.9  2340.1   728.5 2339.42   741.6 2335.72   744.8  2335.5   757.9 2336.75
#Mann= 6 ,-1 , 0
       0    .035       0     200     .06       0     230    .035       0
   346.3    .045       0   375.7    .035       0     450      .1       0
Bank Sta=346.3,375.7
XS Rating Curve= 0 ,0
Exp/Cntr=0.3,0.1

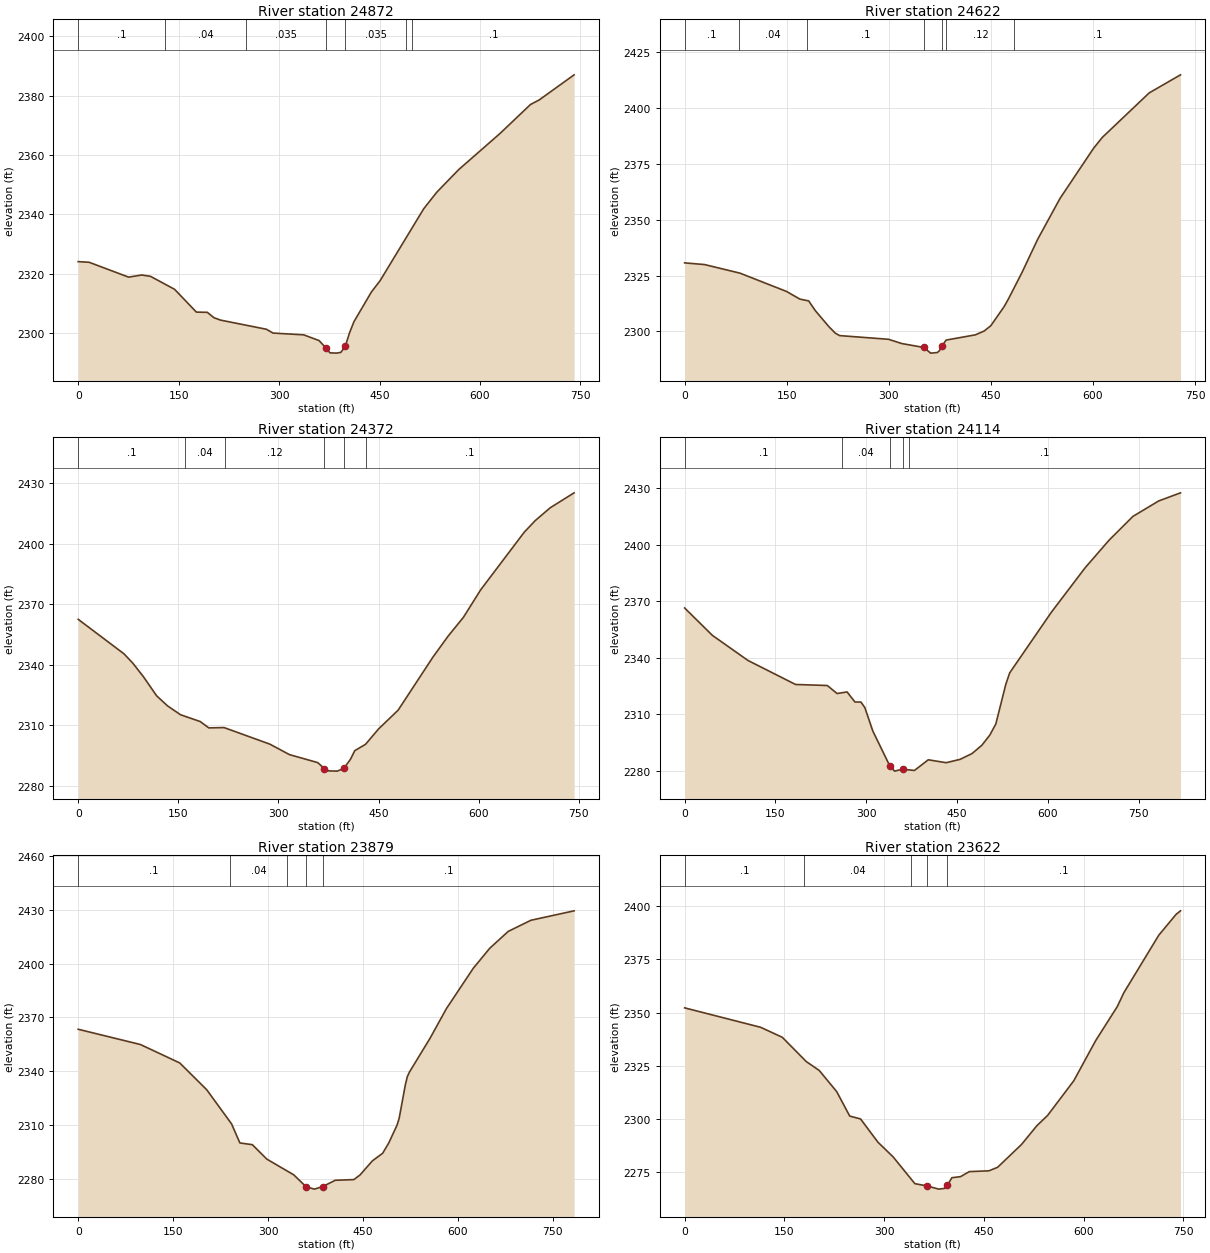
Type RM Length L Ch R = 1 ,24872   ,243.8,250,259.4
XS GIS Cut Line= 3
     2168383.691       243299.67     2168692.059      243079.049
     2168973.629      242852.657
#Sta/Elev= 30
       0 2324.11    16.3  2323.9    75.2 2318.89    94.8 2319.61   107.9 2319.16
   143.8 2314.81   176.5  2307.1   192.8 2307.03   202.7 2305.22   212.5 2304.41
   281.1 2301.32   290.9 2300.04   336.7 2299.44   359.6 2297.52   369.4 2295.17
   375.9 2293.38   385.7 2293.28   392.2 2293.53   398.7 2295.53   405.2 2300.15
   411.7 2303.85   437.8 2313.88   450.8  2317.7   515.9 2341.92   535.4  2347.5
     568 2355.09   629.8 2367.29   675.4 2377.07   688.4 2378.61   740.5 2387.07
#Mann= 7 ,-1 , 0
       0      .1       0     130     .04       0     250    .035       0
   369.4    .045       0   398.7    .035       0  489.16     .12       0
  499.16      .1       0
Bank Sta=369.4,398.7
XS Rating Curve= 0 ,0
Exp/Cntr=0.3,0.1

Type RM Length L Ch R = 1 ,24622   ,249.9,250,246.7
XS GIS Cut Line= 3
     2168417.082      243396.162     2168772.391      243314.091
     2169121.924      243212.911
#Sta/Elev= 30
       0 2330.67    29.3 2329.92    81.4 2326.06   149.8 2317.86   169.3 2314.44
   182.3 2313.62   192.1 2309.25   211.6 2302.21   221.4 2299.17   227.9 2298.08
   299.6 2296.43   319.1 2294.52   351.6 2292.76   361.4 2290.23   371.2 2290.49
   374.5 2291.34   377.8 2293.35   384.3 2296.08     427 2298.41   440.1 2300.13
   449.9 2302.52   469.6 2311.14   476.1  2314.7   495.8 2326.43   518.7 2341.22
   551.5 2359.52   600.7 2381.96   613.8 2386.92   682.6 2406.84   728.6 2414.93
#Mann= 7 ,-1 , 0
       0      .1       0      80     .04       0     180      .1       0
   351.6    .045       0   377.8      .1       0  384.66     .12       0
  484.66      .1       0
Bank Sta=351.6,377.8
XS Rating Curve= 0 ,0
Exp/Cntr=0.3,0.1

Type RM Length L Ch R = 1 ,24372   ,257,257.2,257.2
XS GIS Cut Line= 3
     2168473.208      243648.435     2168840.769       243545.74
     2169175.321      243409.614
#Sta/Elev= 30
       0 2362.43    68.5 2345.35    81.6 2340.78    97.9  2333.9   117.4 2324.55
   133.7 2319.56   153.3 2315.13   182.7 2311.77   195.7 2308.61   218.5 2308.77
     287 2300.57   316.4 2295.37   358.8  2291.4   368.6 2288.48   375.1  2287.3
   388.1 2287.18   397.9 2288.57   407.7 2292.99   414.2  2297.3   430.4 2300.48
     450 2308.12   479.2  2317.4   531.3 2343.68   554.1 2354.11   576.9 2363.38
   602.9 2377.08     668 2405.57   684.2 2411.26     707 2417.72   742.8 2425.14
#Mann= 6 ,-1 , 0
       0      .1       0     160     .04       0     220     .12       0
   368.6    .045       0   397.9     .12       0  431.64      .1       0
Bank Sta=368.6,397.9
XS Rating Curve= 0 ,0
Exp/Cntr=0.3,0.1

Type RM Length L Ch R = 1 ,24114   ,250.7,235.7,213.3
XS GIS Cut Line= 3
     2168543.645      243930.602     2168915.572       243776.89
     2169197.093      243469.885
#Sta/Elev= 30
       0 2366.37    45.8 2351.84   104.7 2338.49   183.2 2325.76   235.6 2325.21
   251.9 2320.95   268.3  2321.8   281.4 2316.44   291.2 2316.44   297.7 2313.47
   310.8 2301.07   338.8 2282.59   346.8 2279.77   359.9  2280.8   379.5 2280.12
   402.4 2285.78     432 2284.25   454.9 2286.01   474.6 2289.08     491 2293.53
   504.1 2298.92     514 2304.82   530.4 2325.79   536.9 2331.94   605.8 2364.15
   661.6 2387.74   700.9  2402.3   740.3 2414.94   782.9 2423.15     819 2427.47
#Mann= 5 ,-1 , 0
       0      .1       0     260     .04       0   338.8    .045       0
   359.9     .04       0     370      .1       0
Bank Sta=338.8,359.9
XS Rating Curve= 0 ,0
Exp/Cntr=0.3,0.1

Type RM Length L Ch R = 1 ,23879   ,249.5,257.2,267.4
XS GIS Cut Line= 3
     2169057.134      244230.676     2169065.312       243801.63
     2169248.852      243498.212
#Sta/Elev= 30
       0 2363.43    98.3 2354.92   160.5 2344.64   203.1  2329.7   242.4 2310.66
   255.5 2300.04   275.2 2299.08   298.1 2291.03   340.7 2282.24   360.3 2275.56
   373.4 2274.29   386.5 2275.75   406.2 2279.22   435.6  2279.6   445.4 2282.21
   464.9 2290.05   481.2  2294.3   490.9 2300.11     504 2310.06   507.2 2313.75
     517 2332.45   520.2 2337.09   523.5 2339.57     556 2358.38     582 2374.99
   624.3  2397.4   650.4 2408.59   679.6 2417.99   715.4 2424.19   783.7 2429.46
#Mann= 5 ,-1 , 0
       0      .1       0     240     .04       0     330      .1       0
   360.3    .045       0   386.5      .1       0
Bank Sta=360.3,386.5
XS Rating Curve= 0 ,0
Exp/Cntr=0.3,0.1

Type RM Length L Ch R = 1 ,23622   ,256.2,250,240.5
XS GIS Cut Line= 3
     2169123.335      244254.055     2169292.117      243922.114
     2169486.397      243603.205
#Sta/Elev= 30
       0 2352.24   114.3  2343.1     147 2338.37   182.9 2326.99   202.5 2322.78
   228.7 2312.85   248.3 2301.33   264.6 2299.98   290.7 2289.05   313.6 2282.12
   346.3 2269.53   364.9 2268.45   382.2 2266.96     392 2267.35   395.3 2268.83
   401.9 2272.32     415 2272.84   428.1  2275.2   457.6 2275.57   470.7 2277.23
   506.7 2287.98   529.6 2296.74     546 2301.67   585.3 2317.94   618.1 2336.78
   650.8 2352.89   660.6 2359.37   713.1 2386.42   739.3 2396.28   745.8 2397.89
#Mann= 5 ,-1 , 0
       0      .1       0     180     .04       0     340      .1       0
   364.9    .045       0   395.3      .1       0
Bank Sta=364.9,395.3
XS Rating Curve= 0 ,0
Exp/Cntr=0.3,0.1

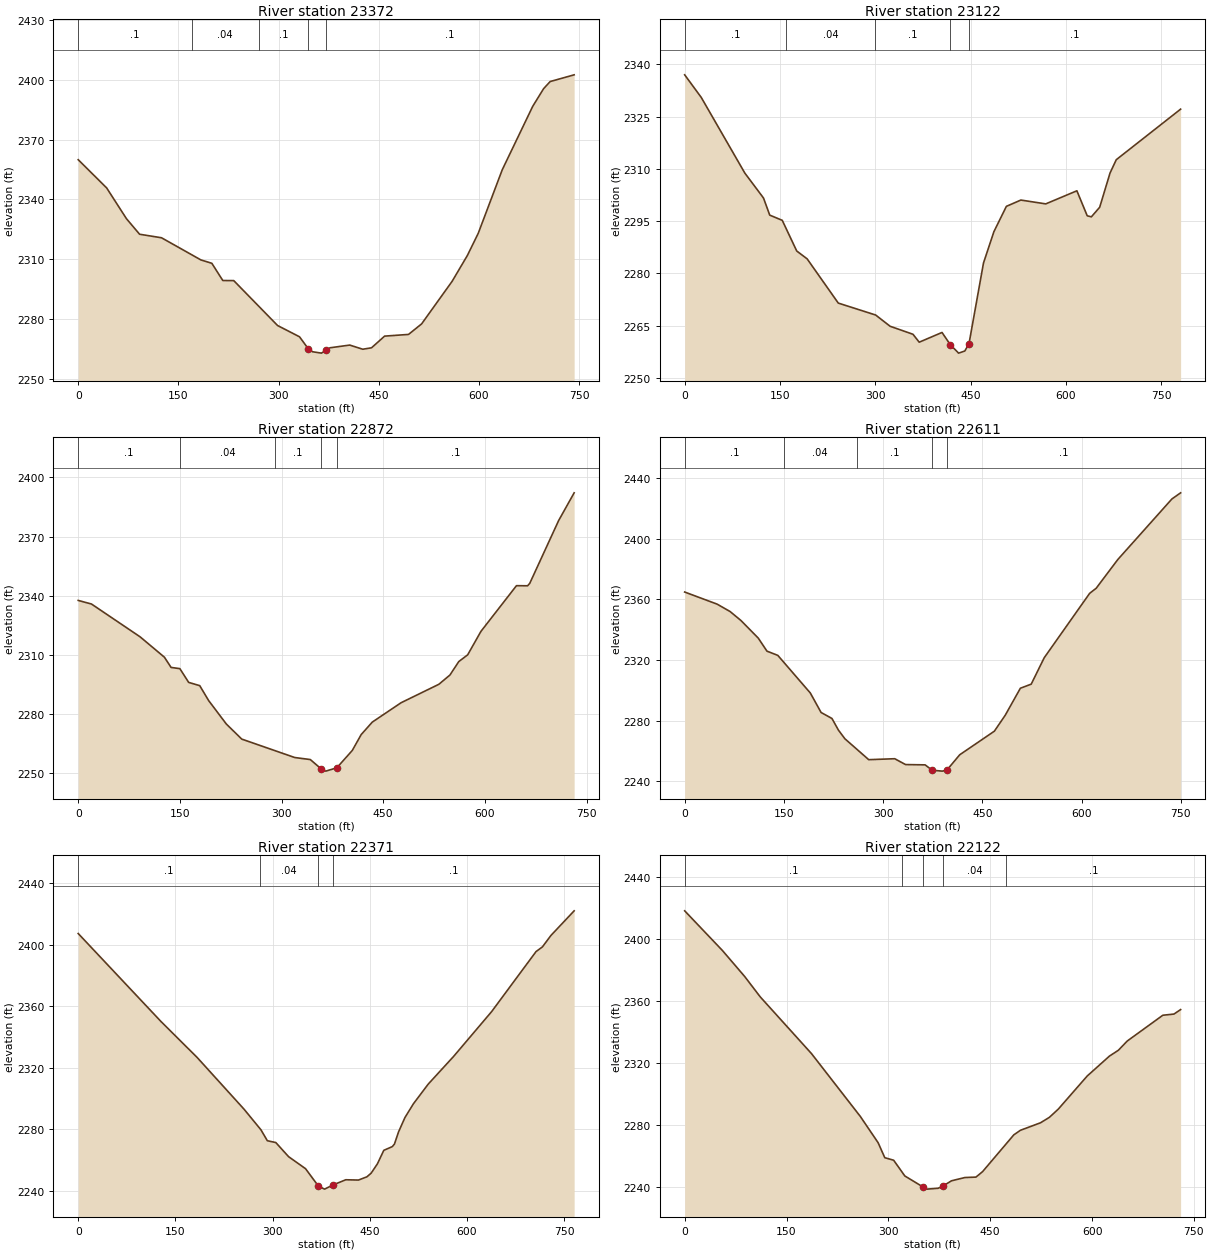
Type RM Length L Ch R = 1 ,23372   ,247.9,250,258
XS GIS Cut Line= 3
     2169484.084      244364.358     2169521.218      244005.401
     2169555.325       243625.21
#Sta/Elev= 30
       0 2359.88    42.6 2345.74    72.2 2330.34    91.9 2322.53   124.7 2320.77
   183.7 2309.66   200.1 2307.97   216.5 2299.34   232.9  2299.3   298.5  2276.8
   331.4 2271.14   344.5 2265.14     351 2263.64   364.1 2262.96   370.7 2264.29
   377.2 2265.65   406.6 2266.99   426.1 2264.91   439.2 2265.63   458.8 2271.48
   494.6 2272.33   514.2 2277.61   559.9 2298.95   582.7 2311.88     599    2323
   634.9 2354.81   680.6 2386.64   696.9 2395.49   706.7 2399.04   742.6 2402.41
#Mann= 5 ,-1 , 0
       0      .1       0     170     .04       0     270      .1       0
   344.5    .045       0   370.7      .1       0
Bank Sta=344.5,370.7
XS Rating Curve= 0 ,0
Exp/Cntr=0.3,0.1

Type RM Length L Ch R = 1 ,23122   ,243.2,250,264.3
XS GIS Cut Line= 3
     2169613.226       244370.49     2169764.943      243970.317
     2169871.886      243634.209
#Sta/Elev= 30
       0    2337    26.1 2330.51    94.7  2308.8   124.1 2301.64   133.9 2296.74
   153.6 2295.24   176.4 2286.44   192.8 2284.18   241.8 2271.49   300.6 2268.07
   323.4 2264.84   359.4 2262.54   369.2 2260.27   405.1 2263.06   418.2 2259.54
   431.2 2257.13     441 2257.74   447.6 2259.85   470.4    2283   486.8 2291.99
   506.4 2299.25   529.2 2301.06   568.4 2299.96   617.4 2303.72   633.7 2296.54
   640.2 2296.24   653.3 2298.99   669.6 2308.82   679.4 2312.64   780.7 2327.15
#Mann= 5 ,-1 , 0
       0      .1       0     160     .04       0     300      .1       0
   418.2    .045       0   447.6      .1       0
Bank Sta=418.2,447.6
XS Rating Curve= 0 ,0
Exp/Cntr=0.3,0.1

Type RM Length L Ch R = 1 ,22872   ,255.2,260.4,264.3
XS GIS Cut Line= 3
     2169663.672      244414.948     2169921.593      244151.825
     2170214.002      243936.368
#Sta/Elev= 30
       0 2337.67    19.6 2335.84    91.3 2319.22   127.2 2308.88     137 2303.71
     150 2303.09     163 2296.12   179.3 2294.47   192.4 2286.93   218.5 2275.04
   241.3 2267.38   319.5 2258.04   342.4 2257.02   358.7 2252.23   365.2 2251.15
   381.5 2252.82   404.4 2261.64   417.5 2269.68   433.9    2276   476.4 2285.82
   532.1 2295.16   548.4 2299.84   561.5 2306.68   574.6 2310.09   594.2 2321.99
   646.6 2345.14     663 2345.08   666.2 2346.32   708.8 2378.13   731.7  2392.2
#Mann= 5 ,-1 , 0
       0      .1       0     150     .04       0     290      .1       0
   358.7    .045       0   381.5      .1       0
Bank Sta=358.7,381.5
XS Rating Curve= 0 ,0
Exp/Cntr=0.3,0.1

Type RM Length L Ch R = 1 ,22611   ,243,240.5,234.2
XS GIS Cut Line= 2
     2169730.676      244511.265     2170415.572      244206.578
#Sta/Elev= 30
       0 2364.84    49.1 2356.85    68.7 2351.97    85.1 2346.05   111.3 2334.43
   124.4 2325.86   140.8 2323.07   189.9 2298.28   206.2 2285.42   222.6 2281.48
   232.4 2273.79   242.2 2268.08   278.2 2254.31   317.5 2254.94   333.9 2251.08
   363.4 2250.89   374.1 2247.34   389.5 2246.76   396.1 2247.33   415.7 2257.53
   468.1  2273.1   484.5  2283.6   507.4 2301.41   523.8 2304.11   543.4 2321.49
   612.1 2363.97     622 2367.34   654.7 2386.29   736.5 2426.23   749.6 2430.25
#Mann= 5 ,-1 , 0
       0      .1       0     150     .04       0     260      .1       0
   374.1    .045       0   396.1      .1       0
Bank Sta=374.1,396.1
XS Rating Curve= 0 ,0
Exp/Cntr=0.3,0.1

Type RM Length L Ch R = 1 ,22371   ,254.3,249.1,243.7
XS GIS Cut Line= 3
     2169944.218      244922.724     2170100.468      244601.109
     2170422.083      244349.807
#Sta/Elev= 30
       0 2407.23   127.9 2349.95   183.7 2326.58   255.9 2293.02   282.1 2279.57
     292 2272.45   305.1 2271.25   324.8 2262.08     351 2254.25   370.9 2242.91
   380.4 2240.96   393.5  2243.7   413.1 2247.05   432.7 2246.86   445.7 2248.97
   452.2  2251.3     462 2257.45   471.8  2266.2   484.9 2268.61   488.2 2270.23
   494.7  2278.3   504.5 2287.57   517.6 2296.51   540.4 2309.27   579.6 2327.29
   638.4 2356.49   706.9  2395.5   716.7 2398.52   729.8 2405.94   765.7 2421.99
#Mann= 4 ,-1 , 0
       0      .1       0     280     .04       0   370.9    .045       0
   393.5      .1       0
Bank Sta=370.9,393.5
XS Rating Curve= 0 ,0
Exp/Cntr=0.3,0.1

Type RM Length L Ch R = 1 ,22122   ,254.8,250,244.1
XS GIS Cut Line= 3
     2170083.596      245070.808     2170285.223      244768.366
     2170511.994      244479.948
#Sta/Elev= 30
       0 2418.33    55.7 2392.62    88.4 2375.85   111.3 2362.68   186.7 2326.04
   258.7 2285.37   284.9 2268.39   294.7  2258.7   307.8 2257.05   324.2  2246.9
   350.4 2239.93   356.9 2238.37   373.3 2238.92   379.9 2240.23     393 2243.76
   412.6 2245.86     429 2246.15   438.8 2249.71   484.7 2273.45   494.5 2276.42
     524 2281.26   537.1 2284.78   550.2 2290.09   592.8  2311.5   625.6  2324.4
   638.7 2328.15   651.8 2334.14   704.2 2350.81   720.6 2351.57   730.4 2354.47
#Mann= 5 ,-1 , 0
       0      .1       0     320     .04       0   350.4    .045       0
   379.9     .04       0  473.49      .1       0
Bank Sta=350.4,379.9
XS Rating Curve= 0 ,0
Exp/Cntr=0.3,0.1