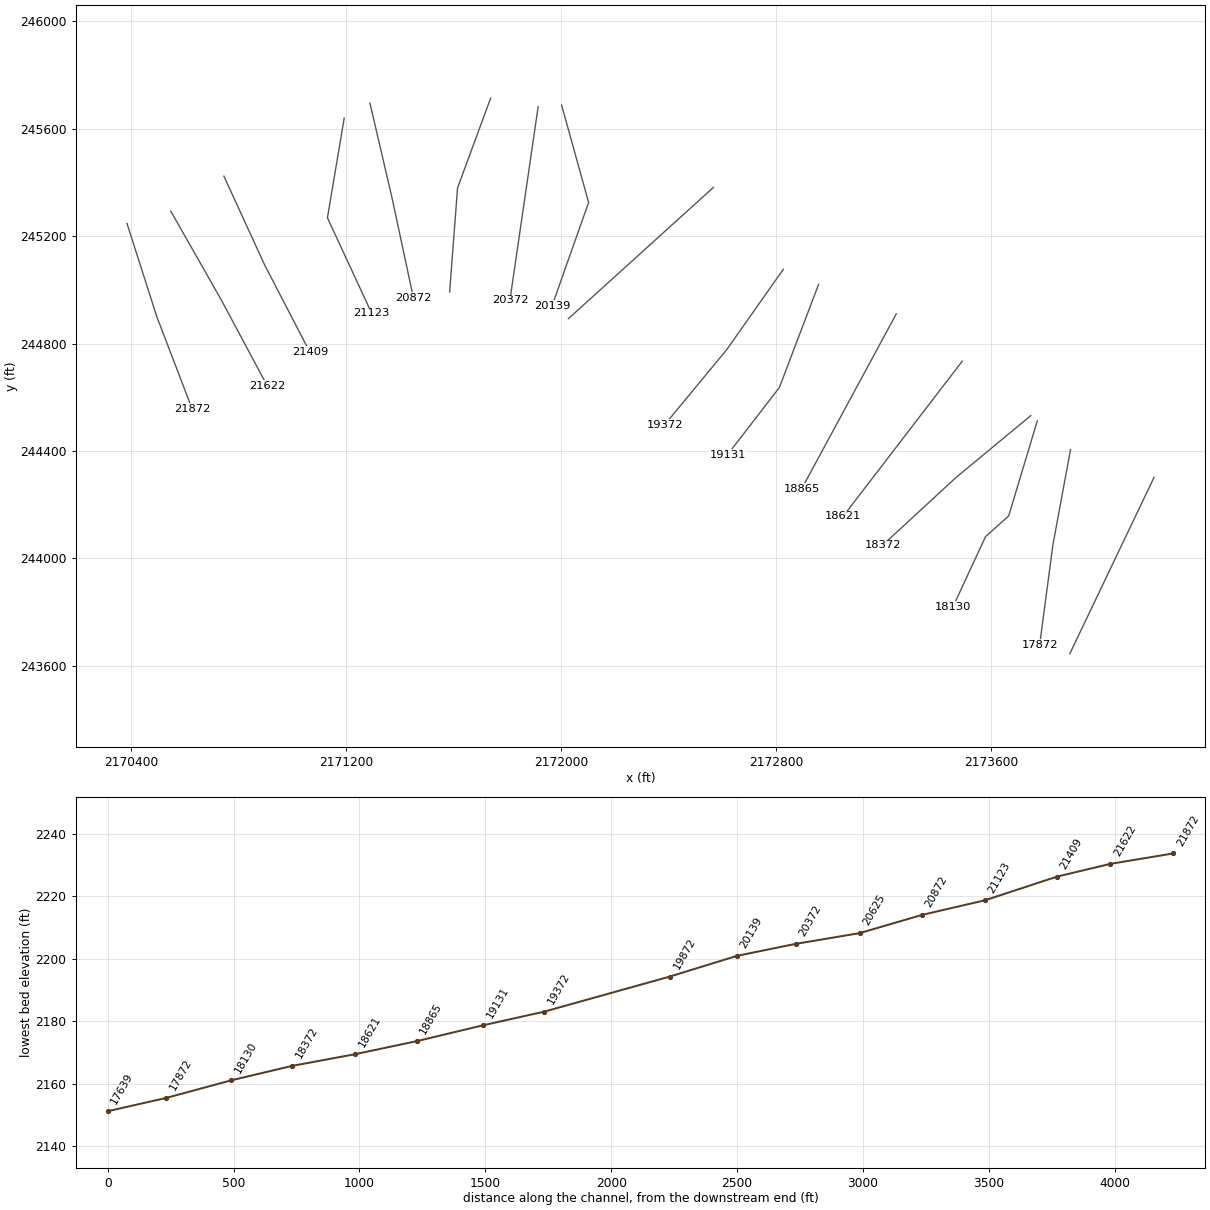
HEC-RAS study COVECK.prj: COVECK

--- COVECK.g01 (geometry) --- (continued)

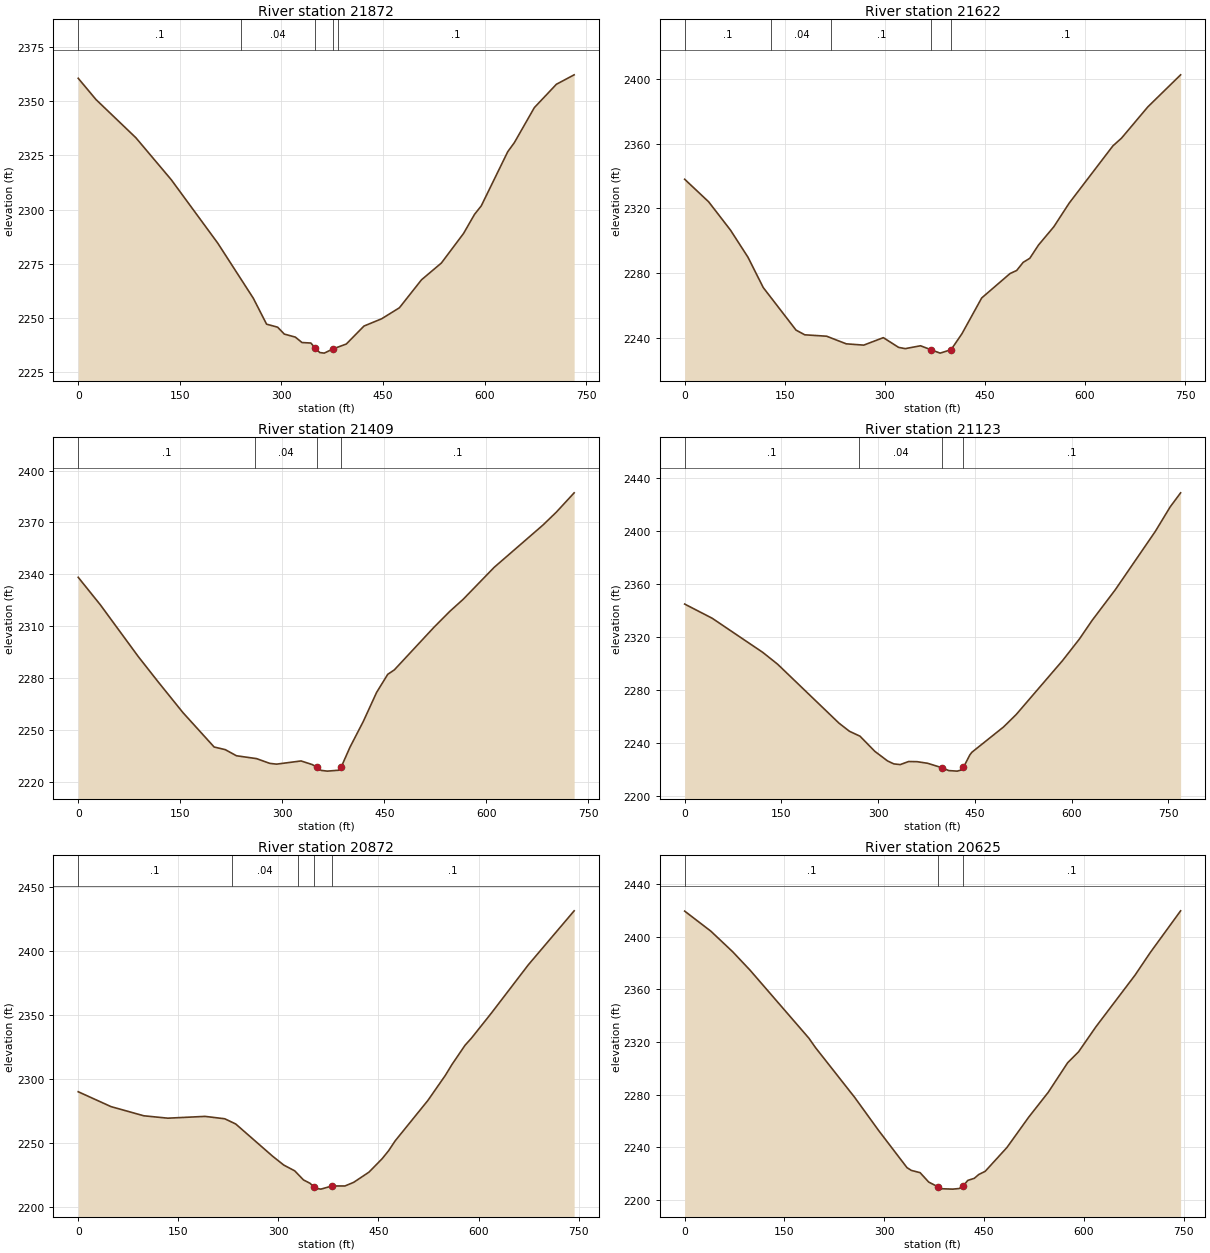
Type RM Length L Ch R = 1 ,21872   ,246.1,250,253
XS GIS Cut Line= 3
     2170384.455      245246.912     2170494.975      244900.989
     2170626.872      244556.357
#Sta/Elev= 30
       0 2360.61    26.2  2350.8    85.1 2333.16   137.4 2313.76   206.1 2284.45
   258.5 2259.06   278.1 2247.07   294.4 2245.68   304.3 2242.49   320.6 2241.09
   330.4 2238.59   343.5 2238.36   350.1 2235.94   356.6 2233.97   363.2  2233.7
   376.2 2235.64   395.8  2237.9   421.9  2246.2     448 2249.56   474.2 2254.64
   506.8 2267.55   536.2 2275.31   568.9 2288.95   585.2 2297.81     595 2301.66
   634.2 2326.72     644 2330.93   673.4 2347.05     706 2357.84   732.2  2362.2
#Mann= 5 ,-1 , 0
       0      .1       0     240     .04       0   350.1    .045       0
   376.2     .04       0  383.15      .1       0
Bank Sta=350.1,376.2
XS Rating Curve= 0 ,0
Exp/Cntr=0.3,0.1

Type RM Length L Ch R = 1 ,21622   ,211.5,212.1,207.9
XS GIS Cut Line= 3
     2170547.145        245293.3     2170736.392      244960.415
     2170906.318      244642.506
#Sta/Elev= 30
       0  2337.9      36 2323.93    68.7 2306.43    94.9 2289.67   117.8  2270.9
   166.9 2244.61     180 2241.69   212.7 2240.83   242.2 2236.11   268.4 2235.31
   297.8 2239.93   320.7 2233.91   330.6 2233.14   353.5 2234.91   369.8 2232.36
   382.9 2230.36   399.3 2232.47   415.7 2242.41   445.2 2264.48   487.8 2279.61
   497.6 2281.46   507.4 2286.51   517.3 2289.01   530.4 2297.24   553.3  2308.5
   576.3 2323.11   641.8 2358.51   654.9 2363.37   694.2 2382.65   743.4  2402.5
#Mann= 5 ,-1 , 0
       0      .1       0     130     .04       0     220      .1       0
   369.8    .045       0   399.3      .1       0
Bank Sta=369.8,399.3
XS Rating Curve= 0 ,0
Exp/Cntr=0.3,0.1

Type RM Length L Ch R = 1 ,21409   ,287.2,286.5,286.3
XS GIS Cut Line= 3
     2170745.184      245423.193     2170896.662       245092.63
     2171064.805      244768.286
#Sta/Elev= 30
       0  2338.3    32.8 2322.26    88.4 2292.43   117.9 2277.69     154 2260.08
   199.8 2240.22   216.2 2238.69   232.6 2235.16   262.1 2233.51   281.7 2230.75
   291.6 2230.32   327.6 2232.16     344 2230.07   351.1 2228.53   357.1 2226.71
   366.1 2226.28   383.2 2226.81   386.4 2228.46   399.5 2240.13   419.1 2255.02
   438.6 2271.76     455 2282.23   464.7  2284.8   523.4 2309.61   546.3 2318.64
   565.9  2325.6   611.5 2344.08   683.3 2368.55   702.9 2375.99     729 2387.12
#Mann= 4 ,-1 , 0
       0      .1       0     260     .04       0   351.1    .045       0
   386.4      .1       0
Bank Sta=351.1,386.4
XS Rating Curve= 0 ,0
Exp/Cntr=0.3,0.1

Type RM Length L Ch R = 1 ,21123   ,253.6,251.4,245.4
XS GIS Cut Line= 3
     2171192.916      245639.737     2171130.416       245268.21
     2171295.346      244912.307
#Sta/Elev= 30
       0 2344.82    42.6 2334.13   121.2 2308.31   144.2 2299.38   239.2 2254.95
   255.5 2248.78   271.9 2245.06   294.8 2233.66   314.5 2226.42   324.3 2224.16
   334.2 2223.64   347.3 2225.95   360.4 2225.83   376.8 2224.62   399.6 2221.15
   409.4 2219.11   422.5  2218.7     429 2219.55   432.3 2221.58   442.1 2230.88
   445.4 2232.97   494.4 2252.03     514  2261.4     586  2302.2   612.1 2318.46
   631.7 2332.44   667.7 2355.64   729.8 2399.72   752.7  2418.1     769  2428.8
#Mann= 4 ,-1 , 0
       0      .1       0     270     .04       0   399.6    .045       0
   432.3      .1       0
Bank Sta=399.6,432.3
XS Rating Curve= 0 ,0
Exp/Cntr=0.3,0.1

Type RM Length L Ch R = 1 ,20872   ,249.5,246.3,237
XS GIS Cut Line= 3
      2171288.62      245695.274     2171370.489      245344.157
     2171450.555      244969.863
#Sta/Elev= 30
       0 2289.94    49.2 2278.33    98.3 2271.19   134.4 2269.32   190.1 2270.72
   219.6 2268.86     236 2264.82   291.7 2239.51   308.1 2232.76   324.5 2228.25
   337.6 2221.18   347.4 2218.55     353 2215.92   357.3 2214.48   363.8 2213.99
   380.2 2216.44   399.8 2216.45   412.9  2219.3   435.8 2227.24   455.4 2237.64
   465.2 2243.94     475  2251.6   524.1 2283.16   550.3 2302.75   560.1 2311.12
   579.7 2326.13   589.5 2331.81     619  2351.1   674.6  2388.9   743.3 2431.03
#Mann= 5 ,-1 , 0
       0      .1       0     230     .04       0     330      .1       0
     353    .045       0   380.2      .1       0
Bank Sta=353,380.2
XS Rating Curve= 0 ,0
Exp/Cntr=0.3,0.1

Type RM Length L Ch R = 1 ,20625   ,254.6,253.7,250.8
XS GIS Cut Line= 3
     2171738.055       245714.39     2171614.791      245379.321
     2171585.277      244992.168
#Sta/Elev= 30
       0 2419.47    39.3 2404.24    72.1 2388.61    98.3 2374.56   186.7 2322.88
   196.5  2315.8   255.5  2277.9   291.5 2252.73   334.1 2224.52   340.6 2222.42
   353.8  2220.7   366.8 2213.52   381.4  2209.8   386.4 2208.48   402.7 2208.19
   412.5 2208.64     419 2210.87   425.5 2214.83   435.3 2216.41   441.9 2219.29
   451.6 2221.72   484.3 2239.83   516.9 2262.81   546.3 2281.74   575.6 2304.29
     592 2312.59     618 2331.55   676.8 2370.81   699.6 2387.92   745.3 2419.69
#Mann= 3 ,-1 , 0
       0      .1       0   381.4    .045       0     419      .1       0
Bank Sta=381.4,419
XS Rating Curve= 0 ,0
Exp/Cntr=0.3,0.1

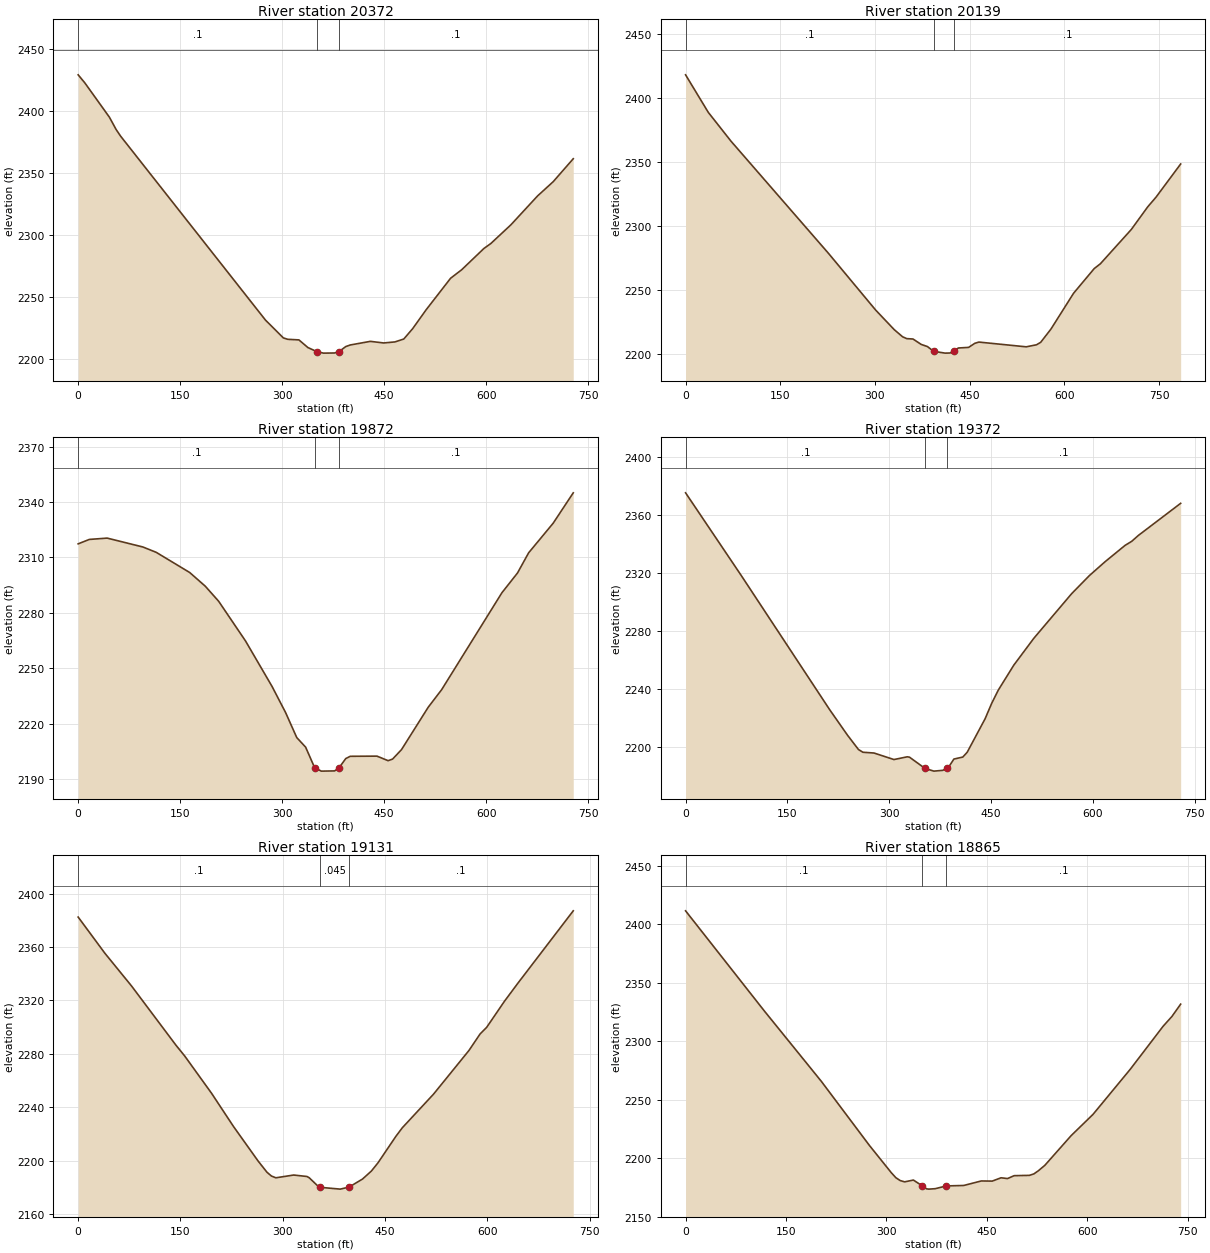
Type RM Length L Ch R = 1 ,20372   ,235.5,232.6,227.2
XS GIS Cut Line= 3
     2171914.801      245682.065     2171862.274      245321.875
     2171809.746      244961.685
#Sta/Elev= 30
       0 2428.81     9.8 2422.33    45.9 2394.73    55.8  2384.8    62.3 2379.52
   275.5 2231.31   301.7 2217.02   308.2 2215.88   324.6 2215.41   337.8 2209.26
   350.9 2205.99   360.7 2204.76   377.1 2204.87   383.7 2206.04   393.5 2210.04
   400.1 2211.32   429.6 2214.23   449.3 2212.95   465.7 2213.78   478.8 2216.11
   491.9 2224.48   511.6  2239.6   547.6 2265.01     564 2271.91   596.8 2289.09
   606.7 2292.95   636.2    2308   675.5 2331.29   698.5 2342.77     728 2361.25
#Mann= 3 ,-1 , 0
       0      .1       0   350.9    .045       0   383.7      .1       0
Bank Sta=350.9,383.7
XS Rating Curve= 0 ,0
Exp/Cntr=0.3,0.1

Type RM Length L Ch R = 1 ,20139   ,275.4,267.4,253.9
XS GIS Cut Line= 3
     2172001.944      245688.349     2172102.638      245325.501
     2171966.817      244941.116
#Sta/Elev= 30
       0 2418.35      36 2389.01      72 2366.49   225.9 2279.15   301.2 2234.52
   330.7 2219.19   343.8  2213.7   350.4 2212.26   360.2 2211.97   373.3 2207.73
   383.1 2206.07   392.9 2202.35   411.1 2200.94     419 2201.05   425.5 2202.85
     432 2204.94   448.3 2205.42   458.1 2208.59   464.6 2209.57   539.6 2205.86
   555.9 2207.46   562.5 2209.39   578.8 2219.77   614.6 2247.73   647.3    2267
     657 2270.73     706 2297.52     732  2315.2   745.1 2322.73   784.2 2348.69
#Mann= 3 ,-1 , 0
       0      .1       0   392.9    .045       0   425.5      .1       0
Bank Sta=392.9,425.5
XS Rating Curve= 0 ,0
Exp/Cntr=0.3,0.1

Type RM Length L Ch R = 1 ,19872   ,495.2,500,502
XS GIS Cut Line= 3
     2172567.092      245381.347     2172297.299      245136.994
     2172027.507      244892.642
#Sta/Elev= 30
       0 2317.38    16.4 2319.77    42.6 2320.49    95.1 2315.69   114.8 2312.78
     164 2301.86   186.9 2294.45   206.6 2286.28     246 2264.84   285.3 2240.03
     305 2226.02   321.4 2212.49   334.5 2207.27   347.6 2196.25   357.4  2194.3
   377.1 2194.42   383.7 2196.15   393.5 2201.11   400.1 2202.33   439.4 2202.42
   455.8 2199.95   462.4 2200.84   475.5 2205.97   514.8 2228.93   534.5 2238.42
   623.1  2290.9     646 2301.59   662.4 2312.52   698.5 2328.57     728 2345.01
#Mann= 3 ,-1 , 0
       0      .1       0   347.6    .045       0   383.7      .1       0
Bank Sta=347.6,383.7
XS Rating Curve= 0 ,0
Exp/Cntr=0.3,0.1

Type RM Length L Ch R = 1 ,19372   ,233.9,241,247.3
XS GIS Cut Line= 3
     2172827.451      245076.645     2172616.903       244777.39
     2172385.291      244497.019
#Sta/Elev= 30
       0  2375.5    81.7 2318.57   212.4 2225.51   238.5 2207.99   254.8 2197.98
   261.4  2196.1   277.7 2195.57   307.1 2191.06   326.7 2192.95     330  2192.7
   352.8 2184.94   365.9 2183.05     379 2183.59   385.6 2185.13   388.8 2186.64
   395.4 2191.39   408.5 2192.77     415 2196.09   441.3 2219.15   451.1 2229.91
   460.9 2239.12   483.8 2256.41   513.3 2274.95     569 2305.79   595.2 2318.32
   618.2 2327.85   647.7 2339.16   657.5 2341.97   667.3 2346.04   729.6 2368.24
#Mann= 3 ,-1 , 0
       0      .1       0   352.8    .045       0   385.6      .1       0
Bank Sta=352.8,385.6
XS Rating Curve= 0 ,0
Exp/Cntr=0.3,0.1

Type RM Length L Ch R = 1 ,19131   ,266.2,265.2,260.5
XS GIS Cut Line= 3
     2172958.541      245019.946     2172812.708      244636.265
     2172619.999      244386.265
#Sta/Elev= 30
       0 2382.48    39.1 2355.44    78.2 2330.92   143.3  2286.6   156.4 2278.33
   195.5 2250.61     228  2225.5   263.9 2199.77   276.9 2191.37   283.4 2188.55
   289.9  2187.2     316 2189.27   335.5  2188.2   338.8 2187.26   351.8 2180.93
   355.1 2180.07   384.4 2178.72   397.4 2180.28     417 2186.26     430 2192.24
   439.8 2198.47   465.8 2218.13   475.5 2224.73   521.1 2249.81   573.2  2282.6
   589.4 2294.89   599.2 2299.95   625.2 2319.42   644.8 2332.88   726.1 2387.16
#Mann= 3 ,-1 , 0
       0      .1       0   355.1    .045       0   397.4      .1       0
Bank Sta=355.1,397.4
XS Rating Curve= 0 ,0
Exp/Cntr=0.3,0.1

Type RM Length L Ch R = 1 ,18865   ,247.2,244.7,239.9
XS GIS Cut Line= 2
     2173247.728      244910.237     2172896.041      244259.529
#Sta/Elev= 30
       0 2411.56   117.8 2325.86   202.9 2265.72   274.9  2210.8   307.6  2187.5
   314.2 2183.38   320.7 2180.92   327.3 2179.83   340.4 2181.36   353.5 2176.46
     360 2173.88   363.3 2173.61   373.1 2173.99   389.5 2176.35   415.6 2176.73
   441.8 2180.59   458.2 2180.47   471.3  2183.3   481.1 2182.65   490.9 2185.11
   513.8 2185.38   520.4 2186.64   526.9 2189.21   536.8 2193.97     576  2219.3
   608.8 2237.55   664.4 2276.09   713.5 2312.87   726.6  2321.2   739.7 2331.77
#Mann= 3 ,-1 , 0
       0      .1       0   353.5    .045       0   389.5      .1       0
Bank Sta=353.5,389.5
XS Rating Curve= 0 ,0
Exp/Cntr=0.3,0.1

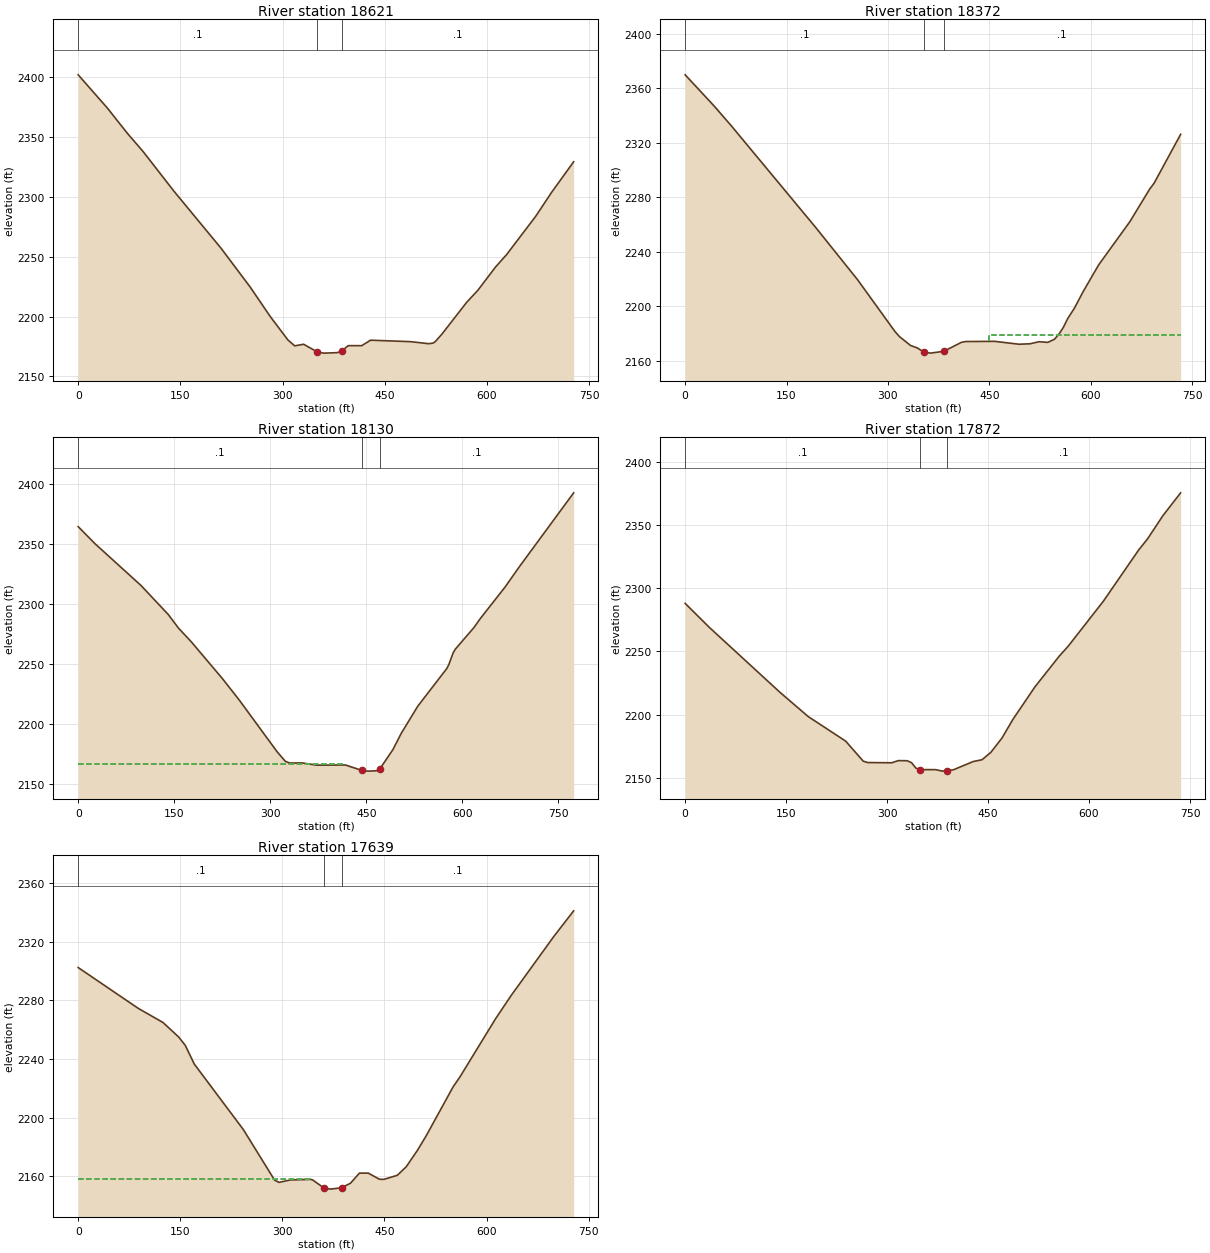
Type RM Length L Ch R = 1 ,18621   ,251.8,249.1,244.4
XS GIS Cut Line= 2
     2173493.325      244734.147     2173050.555      244157.099
#Sta/Elev= 30
       0  2401.7    42.6 2374.14    72.1 2352.97      95 2337.88   140.9 2304.37
   209.7 2256.98   252.3 2224.74   281.8 2200.09     308 2180.34   317.8 2175.51
   330.9 2176.85   350.6 2170.56   360.4 2169.44     380 2169.82   386.6 2171.14
   396.4 2175.67   416.1 2175.66   429.2 2180.24   488.2    2179   514.4 2177.32
   520.9 2177.79   524.2 2179.08     534 2185.34   570.1 2211.77   586.5 2221.76
   612.7 2241.36     629 2251.77   671.6 2283.64   694.6 2303.38   727.3 2329.16
#Mann= 3 ,-1 , 0
       0      .1       0   350.6    .045       0   386.6      .1       0
Bank Sta=350.6,386.6
XS Rating Curve= 0 ,0
Exp/Cntr=0.3,0.1

Type RM Length L Ch R = 1 ,18372   ,239.4,242,239.3
XS GIS Cut Line= 3
     2173748.271      244531.398     2173468.811      244299.846
      2173196.88      244048.802
#Sta/Elev= 30
       0 2369.79    42.5 2347.13    68.7 2332.15   192.9    2258     255 2219.59
   310.6 2181.42   317.2 2177.77   333.5 2171.31   343.3 2169.57   353.1  2166.5
   362.9 2165.72   382.6 2167.06   408.8 2173.65   415.3 2174.22   457.9 2174.36
   493.9 2172.24   510.3 2172.57   523.4 2174.09   536.5 2173.61   546.3 2175.87
   552.9 2179.66   559.4 2184.51     566 2191.12   575.8 2198.63   588.9 2210.95
   611.8 2230.48   657.7 2261.97   687.2 2286.02   693.7  2290.3     733 2326.16
#Mann= 3 ,-1 , 0
       0      .1       0   353.1    .045       0   382.6      .1       0
#XS Ineff= 2 , 0
                          450.17         2178.66
Permanent Ineff=
       F       F
Bank Sta=353.1,382.6
XS Rating Curve= 0 ,0
Exp/Cntr=0.3,0.1

Type RM Length L Ch R = 1 ,18130   ,240,258,266.3
XS GIS Cut Line= 4
     2173772.574      244511.649     2173666.238      244157.916
     2173580.069       244080.71     2173458.541      243818.557
#Sta/Elev= 30
       0 2364.73    26.2 2350.53    98.1 2315.73   140.6  2291.6   156.9 2280.08
   176.5 2268.92   225.5 2238.02   251.7 2220.23   310.5 2177.41   323.6 2169.27
   330.1 2167.86   349.8 2167.94   372.6 2166.05   417.6 2166.19   443.3 2161.65
   452.9 2161.09   465.8 2161.38     471 2162.74   491.6 2178.97   504.6  2192.5
   530.5 2215.18     576 2246.67   579.2 2250.14   585.7 2259.54     589 2262.57
   618.2 2280.65   627.9 2287.97   666.9 2314.45   689.6 2331.65     774 2392.88
#Mann= 3 ,-1 , 0
       0      .1       0   443.3    .045       0     471      .1       0
#XS Ineff= 2 , 0
          413.53 2166.81
Permanent Ineff=
       F       F
Bank Sta=443.3,471
XS Rating Curve= 0 ,0
Exp/Cntr=0.3,0.1

Type RM Length L Ch R = 1 ,17872   ,237.3,233.1,224.1
XS GIS Cut Line= 3
      2173896.38      244405.068     2173830.557      244048.678
     2173781.576      243678.239
#Sta/Elev= 30
       0    2288    35.9 2269.05   140.4 2217.95   182.8 2198.58   238.4  2179.2
   264.5 2163.38     271 2162.25   306.9 2162.06   316.7 2163.78   329.8 2163.68
   336.3 2162.15   342.8 2157.85   349.4 2156.67   372.2 2156.64   382.1 2155.47
   388.6 2155.76   398.5 2156.52     428 2163.06   441.1 2164.47   454.2 2170.34
   470.6 2181.56     487 2196.42   519.8 2222.15   555.8 2246.35   568.9 2254.07
   621.4  2289.8   673.8 2330.24   686.9 2338.95   709.9 2357.42   736.1 2375.36
#Mann= 3 ,-1 , 0
       0      .1       0   349.4    .045       0   388.6      .1       0
Bank Sta=349.4,388.6
XS Rating Curve= 0 ,0
Exp/Cntr=0.3,0.1

Type RM Length L Ch R = 1 ,17639   ,266.3,266.9,267.8
XS GIS Cut Line= 3
     2174207.325      244301.729     2174050.539      243973.226
     2173893.753      243644.724
#Sta/Elev= 30
       0 2302.41    88.5 2274.48   124.6 2264.91   147.6 2255.04   157.4 2249.28
   170.5 2236.61   242.7 2191.82   288.6 2157.32   295.1 2155.81   311.5 2157.44
     341 2157.84   344.3 2157.55   360.7 2152.12   370.6  2151.2     387 2152.12
   400.1 2155.24   413.2 2162.11   426.3 2162.11   442.7 2157.93   449.3 2157.88
   468.9 2160.64     482 2166.46   498.4 2177.62   511.6  2187.8   550.9 2221.02
   560.8 2227.68   613.2 2267.43   636.2 2283.36   698.5 2323.41     728 2341.12
#Mann= 3 ,-1 , 0
       0      .1       0   360.7    .045       0     387      .1       0
#XS Ineff= 2 , 0
          341.59 2157.91
Permanent Ineff=
       F       F
Bank Sta=360.7,387
XS Rating Curve= 0 ,0
Exp/Cntr=0.3,0.1