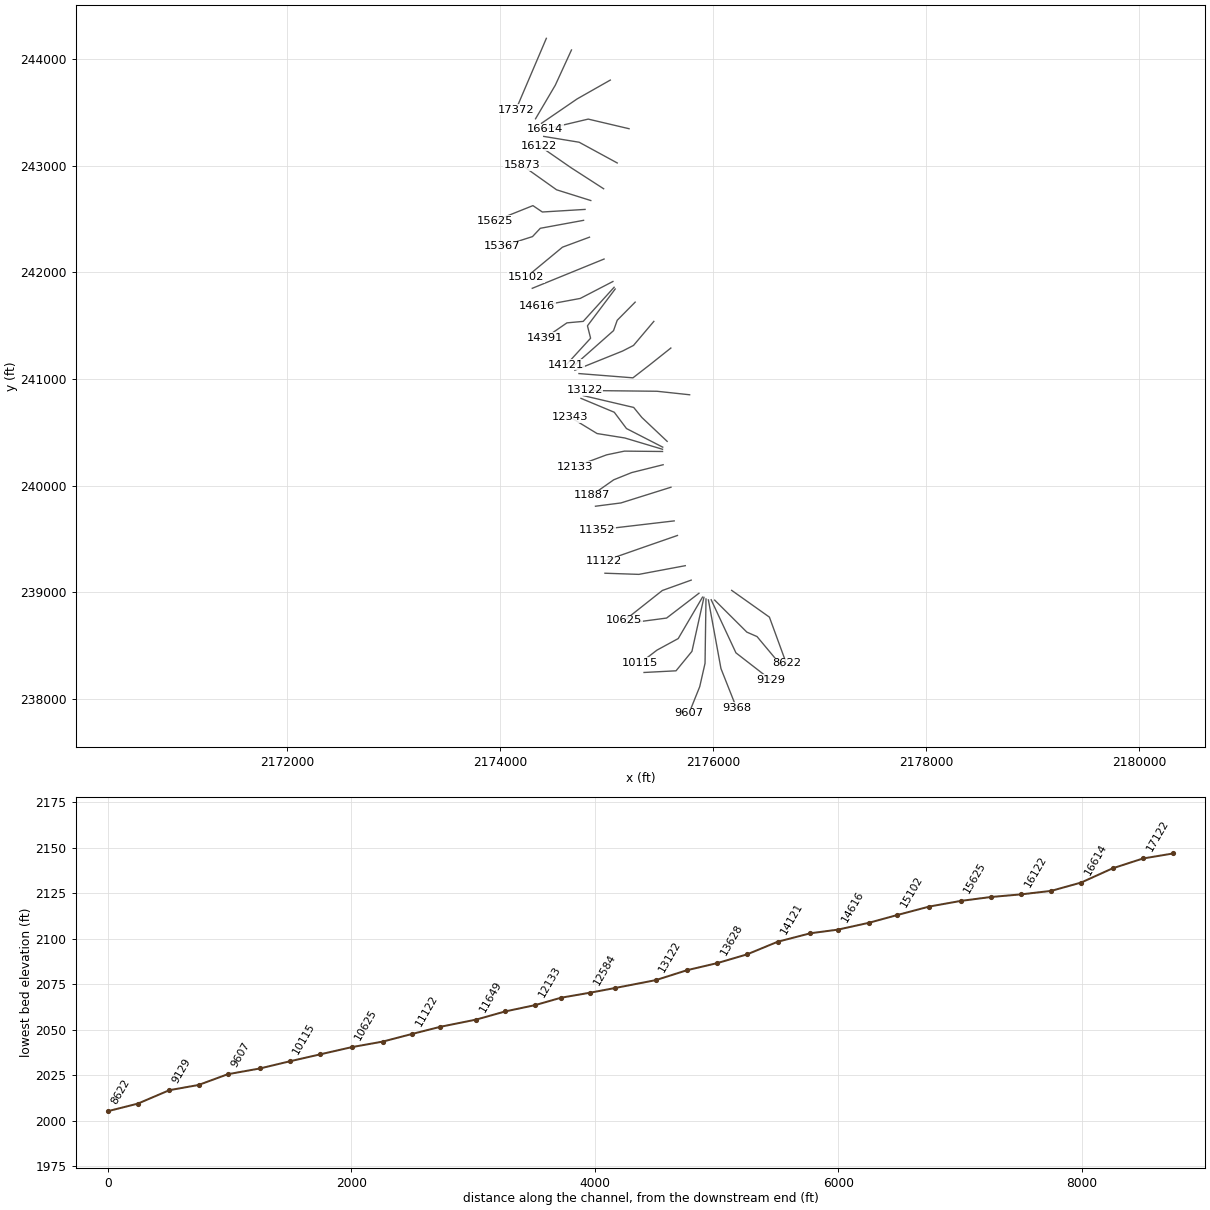
HEC-RAS study COVECK.prj: COVECK

--- COVECK.g01 (geometry) --- (continued)

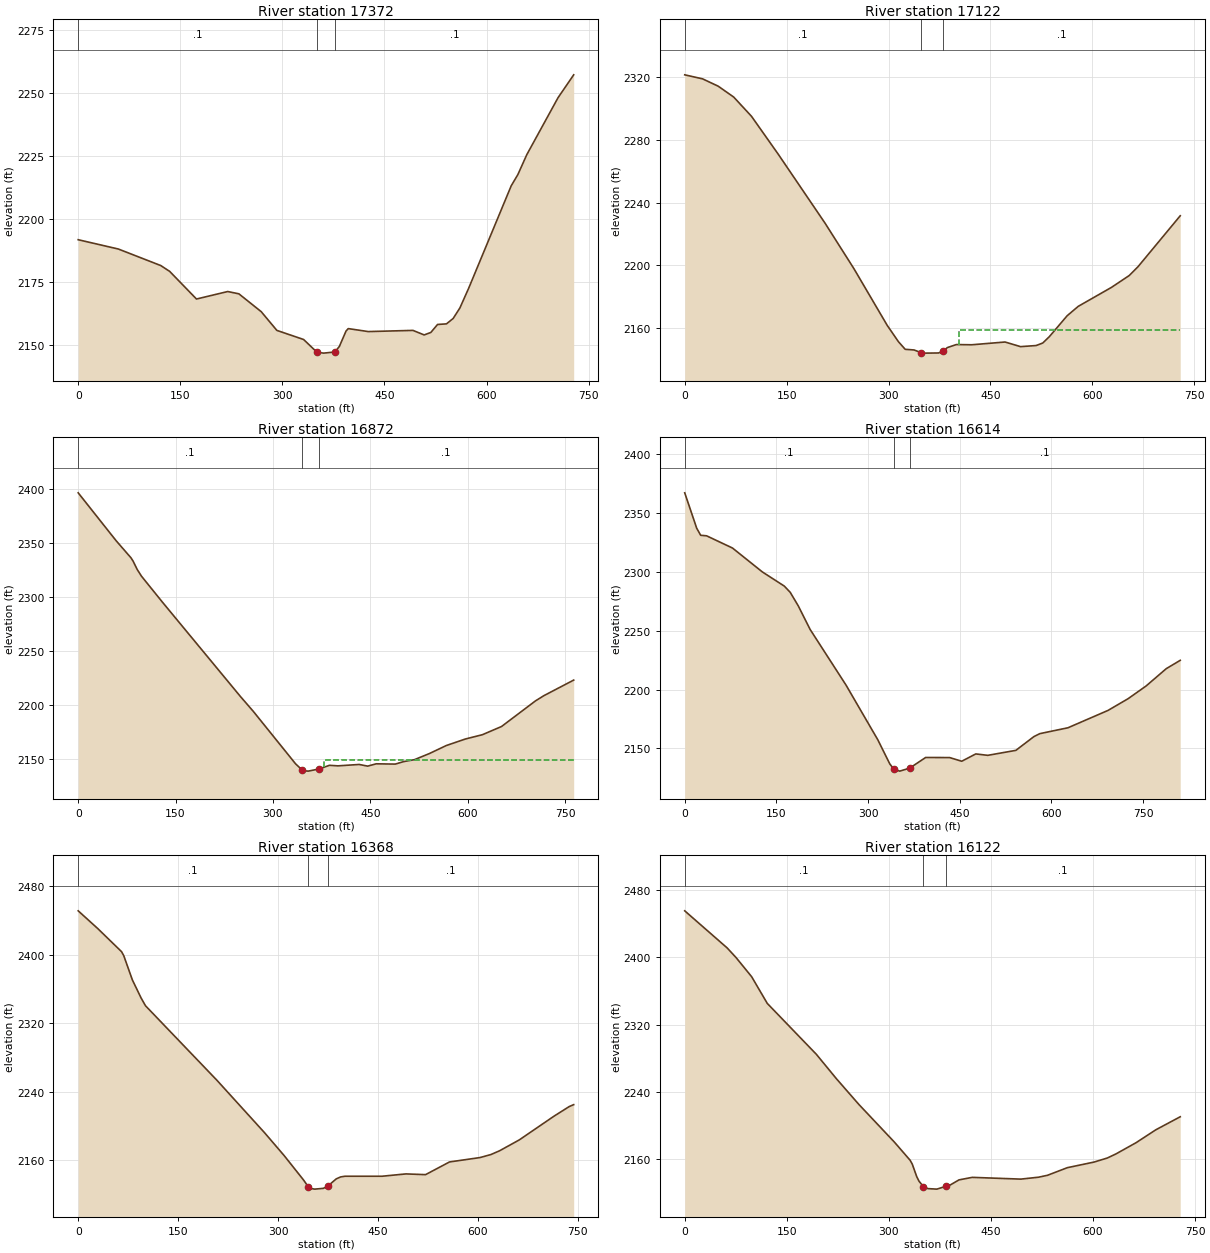
Type RM Length L Ch R = 1 ,17372   ,250.5,250,247.4
XS GIS Cut Line= 3
      2174435.48      244195.893     2174292.547       243861.13
     2174149.614      243526.367
#Sta/Elev= 30
       0 2191.77      59 2188.08   121.3 2181.52   134.4 2179.21   173.8 2168.24
   219.7 2171.21   236.1  2170.3   268.9 2163.22   291.9 2155.79   331.2 2152.18
   350.9  2147.1   360.7 2146.77   377.1 2147.23   383.7 2149.41   393.5 2155.52
   396.8  2156.5   426.3 2155.32   491.9 2155.79   508.3 2153.99   518.1 2154.97
     528 2158.14   541.1 2158.38   550.9 2160.52   560.8 2164.69   573.9 2172.64
   636.2 2213.16     646 2217.63   659.1 2225.52     705 2248.12     728  2257.2
#Mann= 3 ,-1 , 0
       0      .1       0   350.9    .045       0   377.1      .1       0
Bank Sta=350.9,377.1
XS Rating Curve= 0 ,0
Exp/Cntr=0.3,0.1

Type RM Length L Ch R = 1 ,17122   ,261.1,250,241.8
XS GIS Cut Line= 3
     2174671.372      244086.786     2174519.432      243756.245
     2174333.982      243441.229
#Sta/Elev= 30
       0 2321.58    26.2 2319.02    49.2 2314.35    72.1 2307.39    98.3  2295.1
   137.6 2270.95   206.5 2226.94   249.1 2197.83   298.2 2161.58   314.6 2151.25
   324.5 2146.42   337.6 2145.99   347.4 2144.38     354 2143.98   373.6 2144.08
   380.1 2145.23   386.6 2147.53   399.7 2149.44   422.5 2149.31   471.5 2151.07
   494.3 2148.12   517.2 2148.82     527 2150.44   536.8 2154.55   562.9 2167.85
   579.2 2173.83   628.2 2185.96   654.3 2193.52   667.3  2199.2   729.3 2231.63
#Mann= 3 ,-1 , 0
       0      .1       0   347.4    .045       0   380.1      .1       0
#XS Ineff= 2 , 0
                          403.02         2158.44
Permanent Ineff=
       F       F
Bank Sta=347.4,380.1
XS Rating Curve= 0 ,0
Exp/Cntr=0.3,0.1

Type RM Length L Ch R = 1 ,16872   ,270.4,257.8,242
XS GIS Cut Line= 3
     2175035.864      243804.285     2174724.794      243627.873
     2174389.753      243398.864
#Sta/Elev= 30
       0 2396.57    58.5 2352.14    81.3 2336.34    84.5 2333.35      91 2325.45
    97.5  2319.3     130 2295.06   250.3  2207.5   269.8 2193.96   334.8 2145.42
   344.6 2139.84   347.9 2138.93   354.4 2138.56   370.7  2140.5   387.1 2143.94
   400.2 2143.45   432.9 2144.73     446 2143.19   459.1 2145.34   488.5 2145.08
   501.6 2147.41     518 2149.17   540.9  2154.8   567.1 2162.28   596.5 2168.33
   622.7 2172.32   652.2 2179.91   704.5 2203.67   717.6 2208.56   763.4 2222.96
#Mann= 3 ,-1 , 0
       0      .1       0   344.6    .045       0   370.7      .1       0
#XS Ineff= 2 , 0
                          379.37          2149.2
Permanent Ineff=
       F       F
Bank Sta=344.6,370.7
XS Rating Curve= 0 ,0
Exp/Cntr=0.3,0.1

Type RM Length L Ch R = 1 ,16614   ,250.7,245.5,240.5
XS GIS Cut Line= 3
     2175212.013      243348.071     2174828.333      243438.349
     2174422.977      243342.327
#Sta/Elev= 30
       0 2367.27    19.6 2337.19    26.1 2331.19    35.8 2330.73    78.2 2320.34
     127 2300.05   162.9 2288.01   172.6 2282.71   185.7 2271.28   205.2 2251.14
   263.9 2203.89     316 2157.32   335.5 2136.91     342 2132.52   351.8 2130.76
   368.1 2133.33   394.2 2142.36   433.5 2142.27   453.2 2139.16   476.2 2145.38
   495.8 2144.18   541.8 2148.41   571.3  2160.1   581.1 2162.63     627  2167.6
   692.6 2182.36   725.4 2192.31     755 2203.18   787.8 2217.82   810.7 2224.92
#Mann= 3 ,-1 , 0
       0      .1       0     342    .045       0   368.1      .1       0
Bank Sta=342,368.1
XS Rating Curve= 0 ,0
Exp/Cntr=0.3,0.1

Type RM Length L Ch R = 1 ,16368   ,248,246.7,244
XS GIS Cut Line= 3
     2175100.902       243026.89     2174743.263      243221.335
     2174410.808      243275.864
#Sta/Elev= 30
       0 2451.39    29.3 2430.73    65.1 2403.68    68.4 2399.03    81.4  2370.6
    94.4 2349.65     101 2340.54   208.4 2253.33   280.1 2191.88   309.4 2165.25
   338.7 2136.53   345.2  2129.2   348.5 2127.09     355  2126.2     368 2127.09
   374.5 2129.59   387.5 2138.18     394 2140.44   400.6 2141.26   456.1 2141.25
   492.1 2143.97   521.6 2143.13   557.5 2157.94   603.3 2163.08   619.7  2166.6
   632.8 2171.04   662.2 2183.67   714.5 2211.47   737.4 2222.73     744 2224.91
#Mann= 3 ,-1 , 0
       0      .1       0   345.2    .045       0   374.5      .1       0
Bank Sta=345.2,374.5
XS Rating Curve= 0 ,0
Exp/Cntr=0.3,0.1

Type RM Length L Ch R = 1 ,16122   ,248.9,248.2,247.8
XS GIS Cut Line= 3
     2174973.392      242784.882     2174667.459      242982.039
     2174367.895      243189.232
#Sta/Elev= 30
       0 2455.36    62.3 2411.26    75.4 2399.81    98.4 2376.92   121.3 2345.24
   193.5 2284.62     223 2255.56   255.8 2225.14   308.2 2180.16   331.2 2158.68
   334.4 2154.03     341 2139.04   344.3 2133.76   350.8 2127.31   357.4 2124.88
   370.5 2124.28   383.5 2127.56     390 2129.12     403 2135.26   422.5 2138.28
     494 2136.19   520.1 2138.48   533.1 2140.73   562.3 2149.79   601.4 2156.44
   620.9 2161.24   633.9 2166.22   663.2 2179.47   692.4 2194.89   728.2 2210.36
#Mann= 3 ,-1 , 0
       0      .1       0   350.8    .045       0   383.5      .1       0
Bank Sta=350.8,383.5
XS Rating Curve= 0 ,0
Exp/Cntr=0.3,0.1

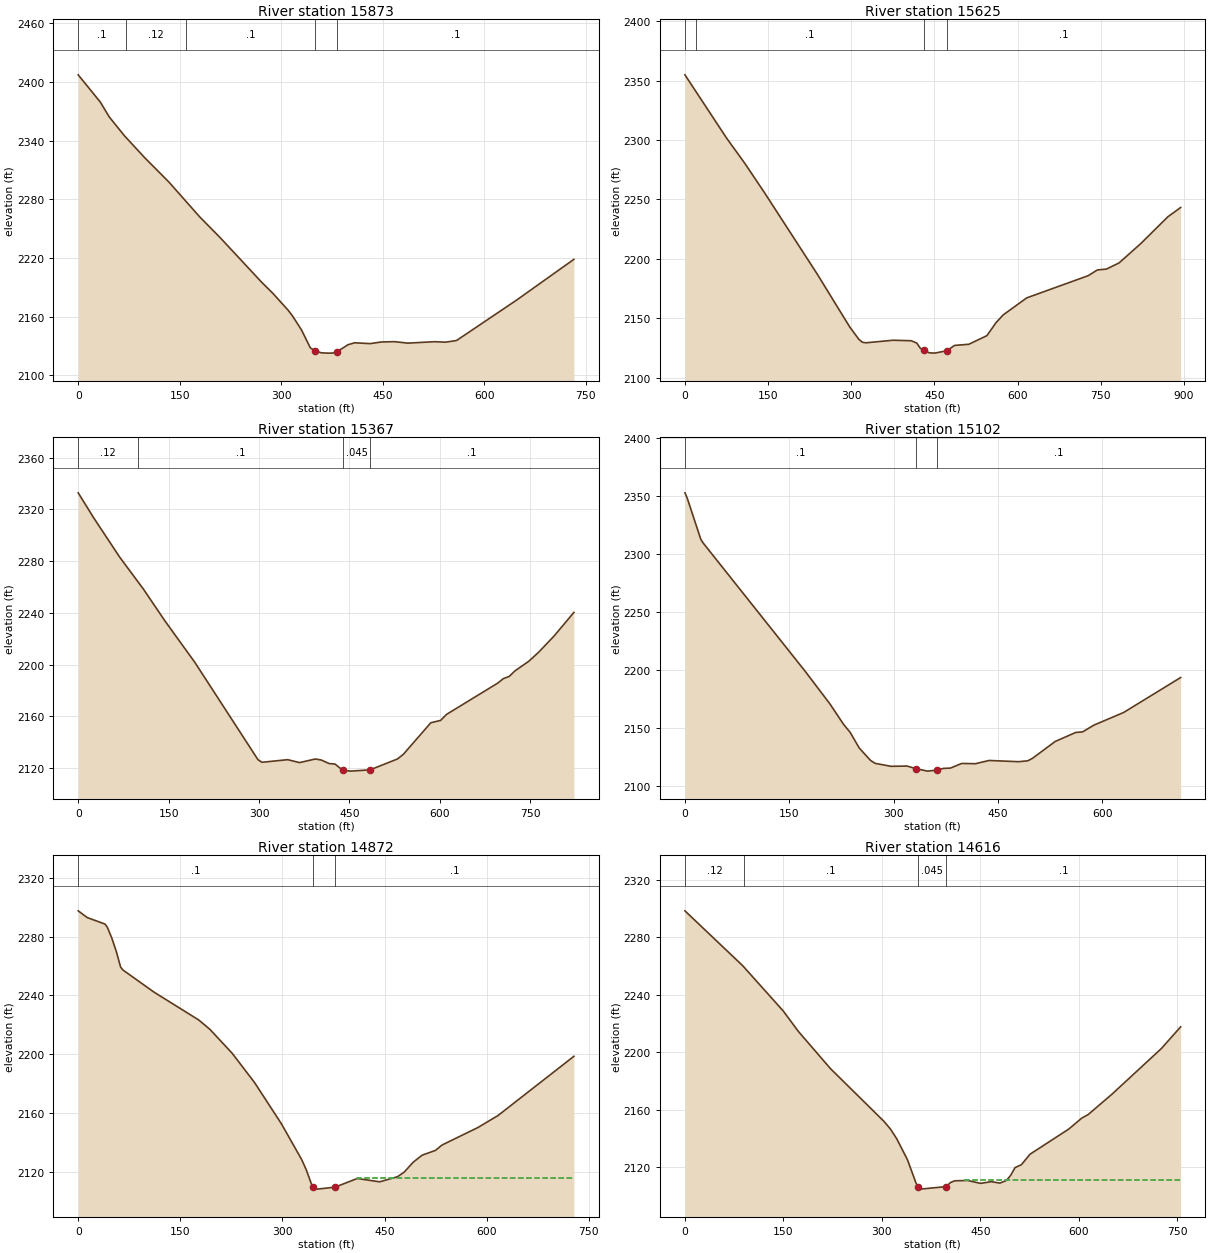
Type RM Length L Ch R = 1 ,15873   ,248,248.8,249.5
XS GIS Cut Line= 3
     2174852.638       242674.46     2174531.458      242775.154
     2174208.541      243004.321
#Sta/Elev= 30
       0 2407.29    32.7 2379.41    45.8 2364.36    68.6 2344.78      98  2322.8
     134 2297.75   179.7 2262.01   209.2 2241.31   271.2 2195.26   287.6 2184.03
   310.4  2166.6     317 2160.56   330.1 2146.42   343.1 2128.23   349.7 2125.32
   359.5 2123.11   369.3 2122.83   375.9 2122.88   382.4 2124.19   398.8 2131.44
   408.6  2133.4   431.5 2132.54   447.9 2134.21   467.5 2134.56   487.1 2133.04
   526.4 2134.51   542.8 2134.02   559.1  2135.7   647.5 2176.83   732.6 2218.72
#Mann= 5 ,-1 , 0
       0      .1       0      70     .12       0     160      .1       0
   349.7    .045       0   382.4      .1       0
Bank Sta=349.7,382.4
XS Rating Curve= 0 ,0
Exp/Cntr=0.3,0.1

Type RM Length L Ch R = 1 ,15625   ,219.5,258.1,295.8
XS GIS Cut Line= 4
     2174798.819      242591.126     2174397.777      242566.821
     2174309.232      242626.676     2173951.596      242483.487
#Sta/Elev= 30
       0 2354.88    75.1 2301.65   107.8 2280.53   143.7 2255.54   238.4 2187.34
   297.2 2142.69   313.6 2132.32   320.1 2129.81   326.6 2129.37   375.6 2131.53
   408.2 2131.09     418 2129.16   424.4 2124.84   430.9 2123.03   440.6 2120.94
   450.4 2120.67     473 2122.74     486 2127.14   511.9 2128.12   544.6 2135.38
   560.9 2146.27     574 2152.86   616.4 2167.17   727.4 2185.88   743.7 2190.66
     760 2191.39   782.9 2196.58   822.1  2212.9     871 2235.47   893.9 2243.22
#Mann= 4 ,-1 , 0
       0     .12       0      20      .1       0   430.9    .045       0
     473      .1       0
Bank Sta=430.9,473
XS Rating Curve= 0 ,0
Exp/Cntr=0.3,0.1

Type RM Length L Ch R = 1 ,15367   ,267.2,264.2,261.3
XS GIS Cut Line= 4
      2174784.93      242488.696      2174378.68      242414.043
     2174305.495       242336.17     2174017.569      242243.904
#Sta/Elev= 30
       0 2332.83    26.2 2313.13    68.8 2283.11   108.2 2258.37   144.2 2233.56
   193.4 2201.77   298.3 2126.39   304.9 2124.42   347.5 2126.44   367.2 2124.18
   393.4 2126.96   403.2 2126.17   416.3 2123.44     426 2123.06     439 2118.22
   451.9 2117.58   484.3 2118.58   529.7 2127.01   539.4  2130.6   584.9 2154.97
   601.2 2156.81     611 2161.45   695.5 2185.52   705.2 2189.09     715 2190.83
   724.7 2195.18   747.5 2202.57   763.8 2209.52   789.8 2222.29   822.3 2240.36
#Mann= 4 ,-1 , 0
       0     .12       0     100      .1       0     439    .045       0
   484.3      .1       0
Bank Sta=439,484.3
XS Rating Curve= 0 ,0
Exp/Cntr=0.3,0.1

Type RM Length L Ch R = 1 ,15102   ,237.5,230.7,225.2
XS GIS Cut Line= 3
     2174840.485       242330.71     2174587.013       242236.96
     2174245.806      241954.903
#Sta/Elev= 30
       0 2353.09     3.3 2348.55    22.8 2313.05      26 2309.96   172.6 2199.34
   208.4 2171.05   227.9  2153.5   237.7 2146.31   250.7 2132.85     267 2122.11
   273.5 2119.62   296.5 2117.04   319.4 2117.27   332.6 2114.99     349 2112.89
   362.1 2113.73   371.9 2115.26   381.8  2115.5   398.1 2119.52   417.8  2119.3
   437.5 2122.08   480.1 2121.03   493.2 2121.82   499.8 2123.89   532.6 2138.48
   562.1 2146.28   571.9 2146.74   588.3  2152.6     631  2163.5     713 2193.67
#Mann= 3 ,-1 , 0
       0      .1       0   332.6    .045       0   362.1      .1       0
Bank Sta=332.6,362.1
XS Rating Curve= 0 ,0
Exp/Cntr=0.3,0.1

Type RM Length L Ch R = 1 ,14872   ,257.8,255.4,247.7
XS GIS Cut Line= 3
     2174977.424      242125.718     2174640.326      241988.383
     2174303.228      241851.048
#Sta/Elev= 30
       0 2297.42    13.1 2292.88    39.4 2288.43    42.6 2286.46    49.2 2279.17
    55.8 2270.08    62.3 2259.26    65.6 2257.33   111.5 2242.23   177.1 2223.37
   193.5 2217.02   226.3 2200.73   259.1 2180.89   298.4 2153.01   327.9 2128.98
   334.5 2122.32   344.3 2109.93   350.9 2108.67   377.1 2109.99   409.9 2115.89
   442.7 2113.62   468.9 2117.08   478.8 2120.22   491.9  2126.9     505 2131.66
   524.7 2134.96   534.5 2138.63     587 2150.44   616.5 2158.57     728 2198.76
#Mann= 3 ,-1 , 0
       0      .1       0   344.3    .045       0   377.1      .1       0
#XS Ineff= 2 , 0
                          409.82          2115.9
Permanent Ineff=
       F       F
Bank Sta=344.3,377.1
XS Rating Curve= 0 ,0
Exp/Cntr=0.3,0.1

Type RM Length L Ch R = 1 ,14616   ,222.1,225.1,216
XS GIS Cut Line= 3
     2175060.549      241914.971      2174753.68      241756.057
     2174350.902      241681.404
#Sta/Elev= 30
       0 2298.49      88 2260.33     150 2228.71   172.8 2214.62   221.7 2188.74
   303.2 2152.06     313 2146.74   322.8 2139.86   339.1 2125.28   352.1 2109.08
   355.4 2106.14   358.7  2104.9     398 2106.66   404.6  2109.5   411.1 2110.69
   430.8  2110.9   450.4  2108.9   466.8 2110.09   479.9 2109.08   489.8 2110.93
   496.3  2114.5   502.9 2119.85   512.7 2121.93   525.8  2129.2   584.8 2146.69
   604.5 2154.27   614.3 2156.76   650.4 2170.86   725.7 2202.62   755.2  2217.8
#Mann= 4 ,-1 , 0
       0     .12       0      90      .1       0   355.4    .045       0
     398      .1       0
#XS Ineff= 2 , 0
                          426.77            2111
Permanent Ineff=
       F       F
Bank Sta=355.4,398
XS Rating Curve= 0 ,0
Exp/Cntr=0.3,0.1

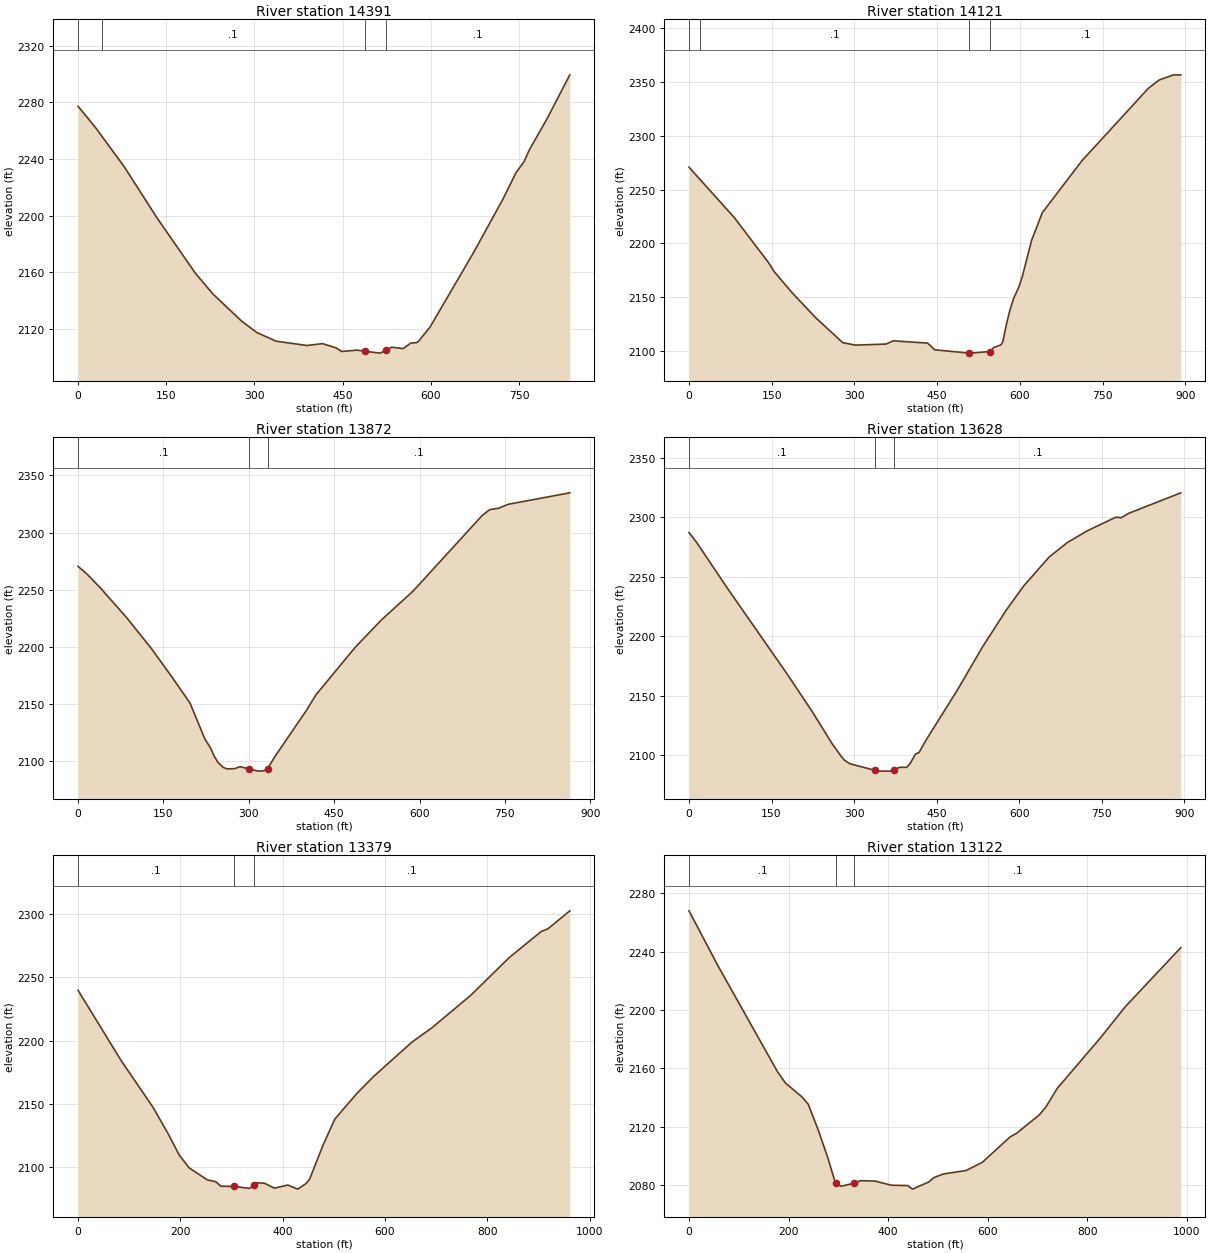
Type RM Length L Ch R = 1 ,14391   ,209.7,269.9,295
XS GIS Cut Line= 4
     2175071.719      241860.855     2174781.458      241540.779
      2174628.68       241526.89     2174422.083      241384.529
#Sta/Elev= 30
       0 2277.24    29.5 2262.35    78.6 2234.55   134.2 2198.51   199.7  2159.3
   229.1 2144.83   278.2 2125.54   304.4 2117.39   337.2 2111.33   389.5 2108.32
   415.7 2109.63   438.6  2106.7   448.4 2104.07   474.5 2105.05   487.6 2104.24
   513.7 2102.92   523.6 2104.88   533.3 2107.11   552.9 2106.14   565.9 2110.01
   575.7 2110.34     579 2111.21   598.5 2121.18   673.5 2174.52   722.4 2211.48
   745.2  2230.6   758.2 2237.81     768 2246.79   797.3 2268.14   836.4 2299.43
#Mann= 4 ,-1 , 0
       0     .12       0      40      .1       0   487.6    .045       0
   523.6      .1       0
Bank Sta=487.6,523.6
XS Rating Curve= 0 ,0
Exp/Cntr=0.3,0.1

Type RM Length L Ch R = 1 ,14121   ,259,249,235.4
XS GIS Cut Line= 4
     2175081.805      241844.599     2174821.388      241499.112
     2174850.902      241382.793     2174621.735      241132.793
#Sta/Elev= 30
       0 2270.68    81.9 2224.11   144.2  2182.2     154 2174.13   186.8 2154.34
   229.4 2131.24   278.6    2108   301.5 2105.66   357.3 2106.64   370.4 2109.65
   432.6 2107.52   445.6 2101.29   507.2 2098.32   510.5 2098.23   546.2 2099.72
   552.6 2103.46   565.7 2105.93     569 2108.58   575.5 2124.81     582 2138.26
   588.5  2148.8   598.3  2159.8   604.8 2170.09   621.1 2202.68   640.7 2228.53
   712.4 2276.66   833.1 2343.95   852.7 2351.61   878.7 2356.37   891.8 2356.28
#Mann= 4 ,-1 , 0
       0     .12       0      20      .1       0   507.2    .045       0
   546.2      .1       0
Bank Sta=507.2,546.2
XS Rating Curve= 0 ,0
Exp/Cntr=0.3,0.1

Type RM Length L Ch R = 1 ,13872   ,257.5,243.8,226.9
XS GIS Cut Line= 4
     2175269.305      241721.335     2175100.902      241551.196
      2175066.18      241453.974     2174675.555      241108.487
#Sta/Elev= 30
       0 2270.52    16.4 2263.44    39.4 2251.57    85.3 2225.69   127.9 2199.26
     164  2174.4   196.8 2150.87     223 2119.38   232.8 2111.65   239.4 2104.38
   245.8 2099.01   255.5 2094.55     262 2093.31   274.9 2093.48   284.6 2095.23
   300.7 2093.24   316.8 2091.35   326.5 2091.65     333 2093.52   345.9 2104.06
   401.7 2144.76   418.1 2158.11   486.9 2199.56   532.8 2223.47   588.6 2248.75
     710 2314.88   723.1 2319.98   739.5 2321.39   755.9 2324.74   864.1 2334.76
#Mann= 3 ,-1 , 0
       0      .1       0   300.7    .045       0     333      .1       0
Bank Sta=300.7,333
XS Rating Curve= 0 ,0
Exp/Cntr=0.3,0.1

Type RM Length L Ch R = 1 ,13628   ,245.1,249.8,253.5
XS GIS Cut Line= 4
     2175444.652      241540.779      2175253.68      241315.085
     2175150.568      241262.303     2174703.333      241082.446
#Sta/Elev= 30
       0 2287.16      13 2279.39    71.5 2239.15   178.7  2167.9   224.2 2136.36
   259.9 2109.68   276.2 2099.19   282.6 2095.68   292.4 2092.76   337.5 2087.26
   343.9 2086.56   366.4 2086.56   372.9 2087.67   382.5 2089.77   395.4 2089.74
   401.8 2092.99   411.5  2100.9     418 2102.29   431.2 2113.07   486.9 2154.24
   532.8 2190.61   575.4 2221.27   608.2 2242.31   654.2 2266.48   686.9 2278.55
     723 2288.44   775.5 2300.03   785.3 2299.56   798.4 2303.19   893.5  2320.5
#Mann= 3 ,-1 , 0
       0      .1       0   337.5    .045       0   372.9      .1       0
Bank Sta=337.5,372.9
XS Rating Curve= 0 ,0
Exp/Cntr=0.3,0.1

Type RM Length L Ch R = 1 ,13379   ,271,257,238.3
XS GIS Cut Line= 4
     2175604.374      241290.779     2175401.249      241129.321
     2175248.471      241011.265     2174741.527      241051.196
#Sta/Elev= 30
       0 2239.81    84.3 2184.24     146 2147.67   175.2 2127.14   197.8 2109.62
   217.3 2099.41     253 2089.92   269.3 2088.52   279.1 2084.94   305.3 2084.77
   334.7 2083.25   344.6 2085.59   351.1 2087.61   364.2 2087.31   383.8 2083.44
     410 2085.87   429.6 2082.64     446  2087.2   452.6 2090.49   478.8 2117.36
   501.8 2137.94   544.4 2158.03   577.2  2171.5   652.7 2198.86     692 2210.26
   767.5 2235.83     843 2265.76   905.3 2286.28   918.4 2288.39   961.1 2302.58
#Mann= 3 ,-1 , 0
       0      .1       0   305.3    .045       0   344.6      .1       0
Bank Sta=305.3,344.6
XS Rating Curve= 0 ,0
Exp/Cntr=0.3,0.1

Type RM Length L Ch R = 1 ,13122   ,349.2,338.2,314
XS GIS Cut Line= 3
     2175780.715      240852.354     2175474.125      240885.291
     2174794.955      240892.558
#Sta/Elev= 30
       0 2267.99      59 2229.78   177.1 2158.04   193.5 2149.97   226.4 2140.57
   239.5 2135.35   259.2    2118   278.8  2098.6     292  2083.6   295.2 2081.19
   305.1 2079.14   331.2 2081.19   344.3 2082.94   373.7  2082.7   406.3 2079.87
     439 2079.62   448.8 2077.18   481.4 2082.07   491.2    2085   510.8 2087.56
   556.5 2089.94   589.2 2095.62   644.7 2112.96   657.8 2115.47   703.5  2128.1
   716.5 2133.42   739.4 2146.24   827.6 2181.48   876.5 2202.42   987.6 2242.77
#Mann= 3 ,-1 , 0
       0      .1       0   295.2    .045       0   331.2      .1       0
Bank Sta=295.2,331.2
XS Rating Curve= 0 ,0
Exp/Cntr=0.3,0.1

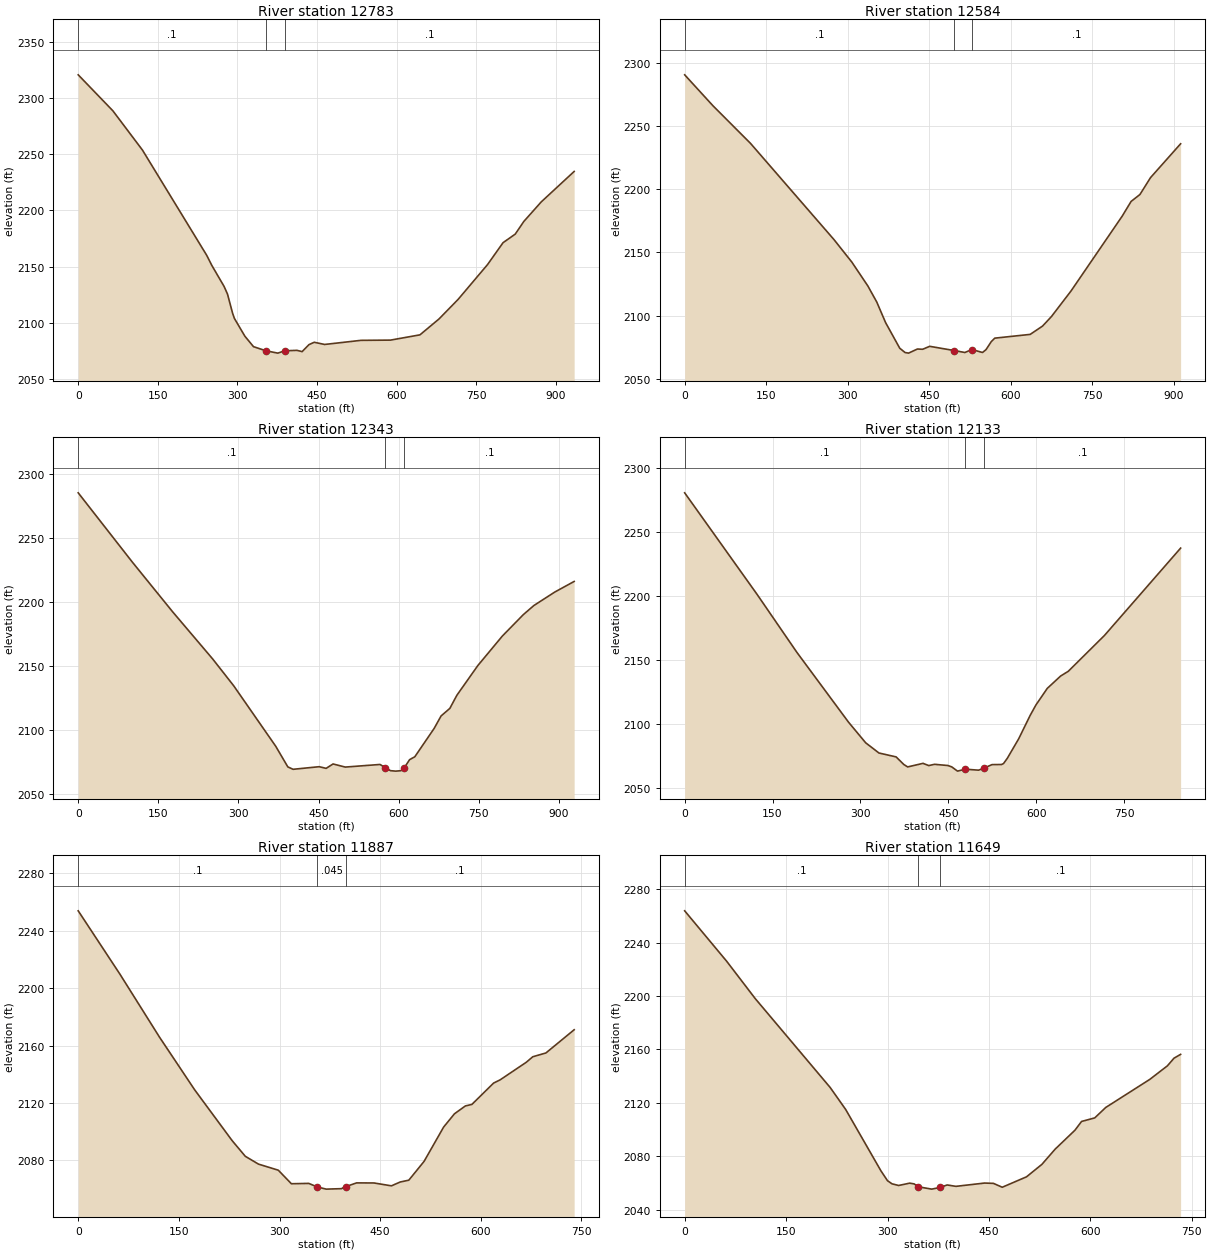
Type RM Length L Ch R = 1 ,12783   ,199.9,199.6,196.1
XS GIS Cut Line= 4
     2175569.693      240415.402     2175331.805      240639.737
     2175255.416      240733.487     2174781.901      240844.497
#Sta/Elev= 30
       0 2320.98    65.4 2288.84     121  2253.9     242 2160.09   251.8 2150.96
   274.7 2132.38   281.2 2125.53     291 2108.11   294.3 2103.73   313.9 2087.94
   330.2 2078.58   353.1 2074.96     376  2072.8   389.1 2074.87     412 2075.28
   421.8 2074.14   434.8  2080.4   444.6 2082.48   464.2 2080.53   532.8  2084.2
   588.3  2084.4   643.8  2089.1   679.7 2103.27   715.6 2120.67   771.1 2151.74
   800.4 2171.31   823.3 2178.93   839.6 2190.28   872.2 2207.61   934.3 2234.81
#Mann= 3 ,-1 , 0
       0      .1       0   353.1    .045       0   389.1      .1       0
Bank Sta=353.1,389.1
XS Rating Curve= 0 ,0
Exp/Cntr=0.3,0.1

Type RM Length L Ch R = 1 ,12584   ,218.3,240.4,253.3
XS GIS Cut Line= 4
     2175528.209      240360.881     2175187.708      240535.571
     2175073.124      240688.349     2174760.643       240818.67
#Sta/Elev= 30
       0 2290.64    52.3 2266.02     121 2236.41   274.8  2160.1   307.5 2142.35
   336.9  2123.5   353.3 2110.77   369.6 2094.43   395.6 2074.17   405.4 2070.77
   411.8  2070.3     428 2073.55   437.7 2073.35   450.7 2075.69     496 2072.32
   515.4 2070.81   528.4 2073.13   547.8  2070.8   554.2 2073.03     564 2079.45
   570.4 2082.16   635.5 2085.13   658.3 2091.73   674.6 2099.26   710.4 2119.37
   804.8 2178.79   821.1 2190.39   837.4  2195.9   856.9 2209.28   912.2 2236.04
#Mann= 3 ,-1 , 0
       0      .1       0     496    .045       0   528.4      .1       0
Bank Sta=496,528.4
XS Rating Curve= 0 ,0
Exp/Cntr=0.3,0.1

Type RM Length L Ch R = 1 ,12343   ,200.2,210.9,218.2
XS GIS Cut Line= 4
     2175526.249      240341.126     2175172.083      240447.029
     2174911.666      240488.696     2174659.628      240641.976
#Sta/Elev= 30
       0 2285.23   101.4    2231   176.6 2192.24   251.9 2155.17   291.2 2134.22
   369.7 2087.01   392.4 2070.83   402.2 2068.95   451.1 2070.98   464.1 2069.69
   477.1 2073.12   499.9 2070.69     565 2072.73   574.8 2070.28   584.6 2067.87
   594.3 2067.52   604.1 2067.86   610.6 2070.31   620.4  2076.5   630.1 2078.74
   666.2 2100.85   679.3 2110.68   695.7  2116.6   708.8 2126.83   748.1 2150.11
     794 2173.19   833.3 2189.96     853 2197.07   892.3 2207.65   928.4  2215.9
#Mann= 3 ,-1 , 0
       0      .1       0   574.8    .045       0   610.6      .1       0
Bank Sta=574.8,610.6
XS Rating Curve= 0 ,0
Exp/Cntr=0.3,0.1

Type RM Length L Ch R = 1 ,12133   ,239.8,245.8,245.1
XS GIS Cut Line= 4
     2175526.249      240320.293      2175168.61      240323.765
     2175001.944      240289.043     2174703.333      240177.932
#Sta/Elev= 30
       0 2280.97   123.6  2201.6   191.8 2156.13   279.6 2101.78   308.9 2085.64
   331.6 2077.64   360.9  2074.6     374 2068.68   380.6 2066.76   406.8 2069.56
   416.6 2067.81   426.4  2068.8   449.3 2067.86   455.9 2066.78   465.7 2063.48
   478.8 2064.98   501.7 2064.23   511.5 2065.96   524.6 2068.57   540.9 2068.65
   544.2 2069.39   550.7 2073.52   570.2 2088.82   589.7 2107.04   599.4 2115.08
   618.9 2128.14   641.7  2137.8   654.7 2141.47   716.5  2169.5   846.5 2237.76
#Mann= 3 ,-1 , 0
       0      .1       0   478.8    .045       0   511.5      .1       0
Bank Sta=478.8,511.5
XS Rating Curve= 0 ,0
Exp/Cntr=0.3,0.1

Type RM Length L Ch R = 1 ,11887   ,238.9,237.4,235.7
XS GIS Cut Line= 4
     2175531.982      240196.137     2175236.319      240122.376
     2175067.916      240054.668     2174860.974      239909.367
#Sta/Elev= 30
       0 2253.85    62.3 2209.65   121.2 2165.83   173.7 2129.08   229.4 2093.79
     249 2082.88   268.7 2077.42   298.2 2073.19   317.7 2063.76   343.6    2064
   356.6 2061.47   369.6 2060.01   392.2 2060.33   398.7 2061.76   414.9 2064.35
   440.8  2064.3   466.8  2062.3   479.8 2064.96   492.7 2066.24   515.4 2079.31
   544.6 2103.25   560.8 2112.51     577 2117.95   586.7 2119.01   619.1 2133.89
   628.9 2136.15   667.8 2148.38   677.5 2152.22     697 2154.84   739.1 2171.01
#Mann= 3 ,-1 , 0
       0      .1       0   356.6    .045       0   398.7      .1       0
Bank Sta=356.6,398.7
XS Rating Curve= 0 ,0
Exp/Cntr=0.3,0.1

Type RM Length L Ch R = 1 ,11649   ,300,297.5,291.8
XS GIS Cut Line= 3
     2175605.496      239985.103     2175135.624      239837.654
     2174896.627      239806.852
#Sta/Elev= 30
       0 2263.73      62 2226.08   104.4 2198.04   215.2 2131.56   238.1 2115.13
   290.3 2069.17     300 2061.82   306.6 2059.52   316.4 2058.28   332.7 2060.02
   339.2 2059.48   345.7 2057.29   365.3 2055.55   378.3 2056.88   388.1 2058.66
   401.2 2057.63   443.5 2060.09   456.6 2059.86   469.6 2056.95   505.5 2064.75
   528.3 2074.09   547.8 2085.42   577.1  2099.6   586.9 2106.17   606.4 2108.83
   622.7 2116.64   687.8 2137.63   713.9  2147.8   723.7 2153.53   733.4 2156.35
#Mann= 3 ,-1 , 0
       0      .1       0   345.7    .045       0   378.3      .1       0
Bank Sta=345.7,378.3
XS Rating Curve= 0 ,0
Exp/Cntr=0.3,0.1

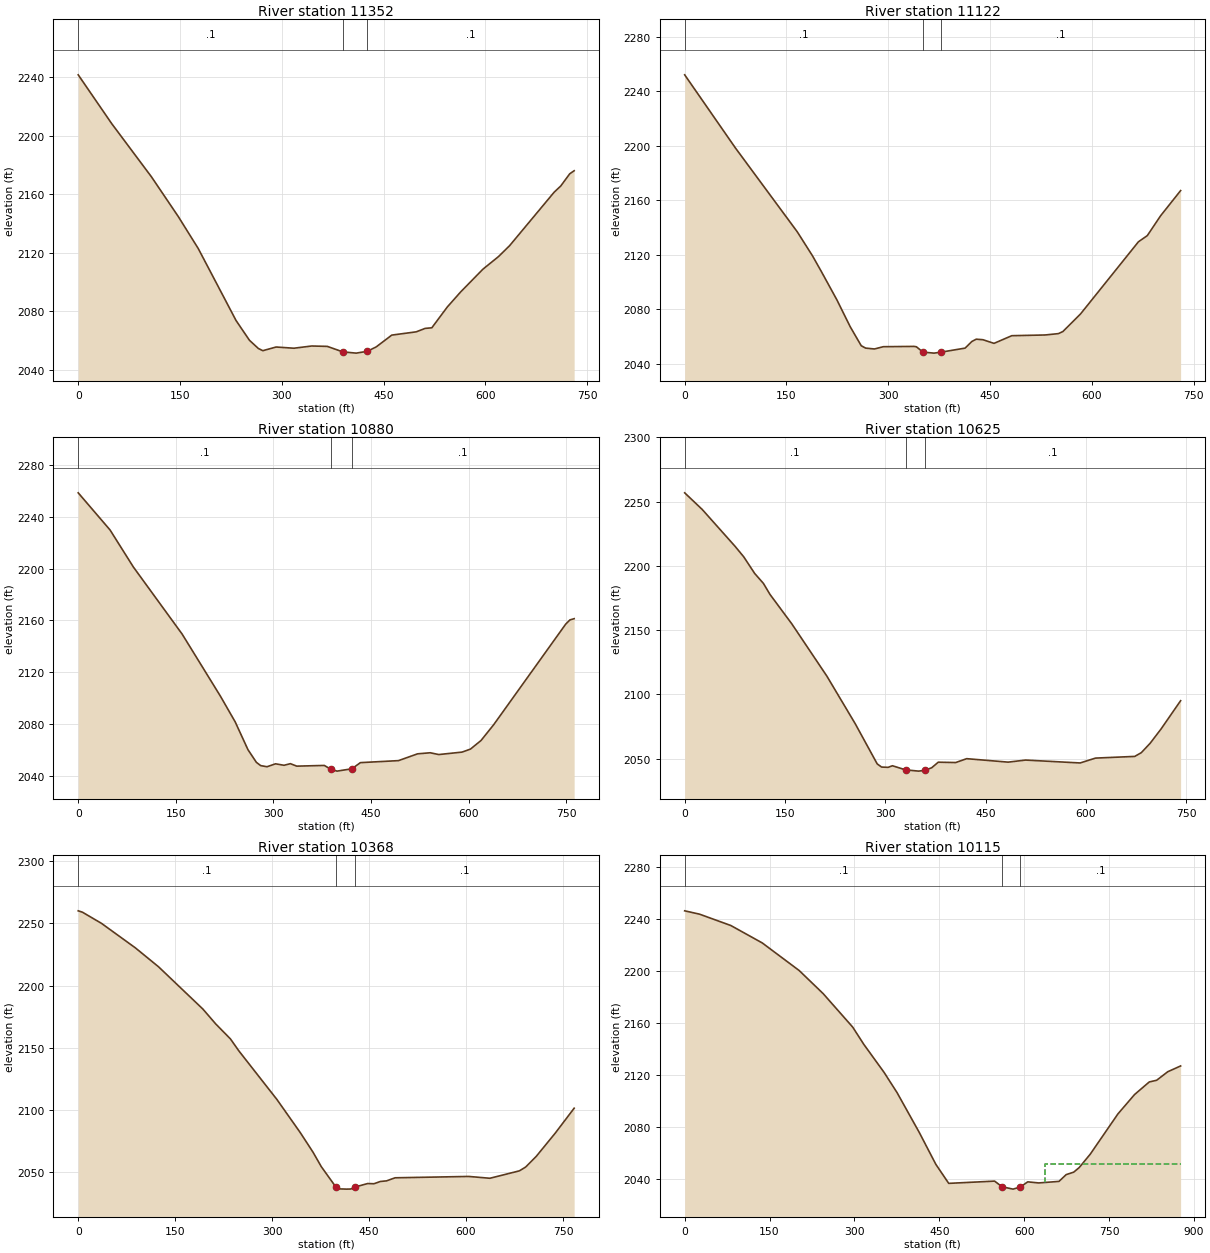
Type RM Length L Ch R = 1 ,11352   ,225.6,230.2,236.6
XS GIS Cut Line= 2
     2175635.624      239669.251      2174909.93      239584.182
#Sta/Elev= 30
       0 2241.46    49.2 2208.26   108.1 2171.72   147.4 2144.77   176.9 2122.88
   232.6 2073.76   252.3 2060.31   265.4  2054.7     272  2053.2   291.6  2055.7
   317.8 2054.88     344 2056.39     367 2056.13   389.9 2052.38   409.6 2051.53
     426 2052.79     439 2055.76     462 2063.83     498 2066.06   511.1  2068.4
     521 2068.82   543.9 2083.07   563.6 2093.36   596.3 2108.82   619.3 2117.45
   635.6 2124.86   701.2 2161.34     711 2165.61   724.1 2173.87   730.7    2176
#Mann= 3 ,-1 , 0
       0      .1       0   389.9    .045       0     426      .1       0
Bank Sta=389.9,426
XS Rating Curve= 0 ,0
Exp/Cntr=0.3,0.1

Type RM Length L Ch R = 1 ,11122   ,244,241.6,239.4
XS GIS Cut Line= 3
     2175666.347      239532.576     2175322.259      239413.109
     2174976.211      239291.908
#Sta/Elev= 30
       0 2252.05    74.8 2198.32   165.9 2136.77   188.6 2118.92   201.6 2107.42
   224.4  2086.7   243.9 2067.08   260.2 2053.08   266.7 2051.33   279.7 2050.69
   292.7 2052.36   338.2 2052.58   341.5  2052.3   351.2 2048.38   367.5 2047.64
   377.3 2048.31   413.3 2051.32   423.2 2056.18   429.7 2057.88   439.5 2057.49
   455.9 2054.82   482.1 2060.44   531.2 2060.97   550.8 2061.96   557.4  2063.5
   583.6 2076.54   668.7  2129.4   681.8 2133.95   701.4 2148.52   730.9 2167.02
#Mann= 3 ,-1 , 0
       0      .1       0   351.2    .045       0   377.3      .1       0
Bank Sta=351.2,377.3
XS Rating Curve= 0 ,0
Exp/Cntr=0.3,0.1

Type RM Length L Ch R = 1 ,10880   ,245.8,254.7,265
XS GIS Cut Line= 3
     2175739.791      239249.112     2175304.027      239167.515
     2174985.504      239178.389
#Sta/Elev= 30
       0 2258.64    48.9 2229.94    84.8 2201.24   159.7 2149.39   218.4 2101.48
   241.2  2081.5   260.8 2060.04   273.8 2050.19   280.4 2047.69   290.1 2046.83
   303.2 2049.09   316.2 2047.95     326 2049.19   335.8 2047.28   378.1 2047.83
   387.9 2044.97   397.7 2043.43   420.5 2045.25   433.6    2050   492.1 2051.55
   521.4  2056.8   540.9 2057.63   553.9 2056.25   589.7 2058.13   602.7 2060.47
     619 2067.16   638.5 2079.42     749 2157.09   755.5 2160.35     762 2161.32
#Mann= 3 ,-1 , 0
       0      .1       0   387.9    .045       0   420.5      .1       0
Bank Sta=387.9,420.5
XS Rating Curve= 0 ,0
Exp/Cntr=0.3,0.1

Type RM Length L Ch R = 1 ,10625   ,266.7,257.7,246.3
XS GIS Cut Line= 3
     2175795.346      239113.696     2175524.513      239016.474
      2175168.61      238735.224
#Sta/Elev= 30
       0 2256.82    26.2  2243.9    75.2  2215.3    88.3 2207.04   104.6 2194.15
   117.7 2186.39   127.5 2177.84   160.2 2154.89   212.6 2114.24   255.1 2077.13
   287.8 2046.02   294.3 2043.54   304.1 2043.33   310.6 2044.56   330.2 2041.36
   349.8 2040.38   359.6 2041.06   369.3 2043.02   379.1 2047.32   405.2 2047.06
   421.6 2050.06   483.6 2047.37   509.7 2048.98   591.2 2046.73   614.1 2050.51
   672.8 2051.82   682.6 2054.72   695.7 2061.95     712 2073.04   741.4 2095.15
#Mann= 3 ,-1 , 0
       0      .1       0   330.2    .045       0   359.6      .1       0
Bank Sta=330.2,359.6
XS Rating Curve= 0 ,0
Exp/Cntr=0.3,0.1

Type RM Length L Ch R = 1 ,10368   ,243.1,252.8,258.7
XS GIS Cut Line= 3
     2175868.263      238990.432     2175564.444      238757.793
     2175183.116      238707.304
#Sta/Elev= 30
       0 2260.06     6.5 2258.97      36 2249.99    88.3 2230.36   124.3 2215.09
     193 2181.07   212.6 2169.26   235.5 2157.16   248.6 2147.49   307.4  2108.5
   343.4 2081.98     363 2066.36   376.1 2054.49     399 2037.89   405.5 2036.61
   415.3 2036.44   421.8 2036.53   428.3 2038.12   447.8 2040.92   457.6 2040.77
   467.4 2042.57   477.2  2043.1   490.2 2045.54   604.3 2046.63   636.9 2045.17
   682.6 2051.13   692.3  2054.2   708.6 2062.72     738  2081.4   767.3 2101.46
#Mann= 3 ,-1 , 0
       0      .1       0     399    .045       0   428.3      .1       0
Bank Sta=399,428.3
XS Rating Curve= 0 ,0
Exp/Cntr=0.3,0.1

Type RM Length L Ch R = 1 ,10115   ,235.8,243,253.3
XS GIS Cut Line= 4
     2175901.481      238953.923     2175673.616      238565.468
     2175473.963      238456.961      2175316.18      238335.918
#Sta/Elev= 30
       0 2246.38    26.1 2243.84    81.6 2235.09   137.1 2221.71   202.3 2200.53
   244.8 2182.74     297    2157   316.6 2143.77   352.4 2122.24   375.3 2106.72
   414.5 2076.17   443.8 2051.66   466.6 2036.99   547.7 2038.73   560.7 2034.42
   580.2 2032.57   593.2 2034.18   606.2 2038.16   625.6 2037.32   661.4 2038.51
   674.3 2043.75   687.4 2045.59   697.2 2049.14   716.7 2059.42   765.6 2090.35
     795 2105.23     821 2114.91   834.1 2116.21   853.6 2122.74   876.4  2127.2
#Mann= 3 ,-1 , 0
       0      .1       0   560.7    .045       0   593.2      .1       0
#XS Ineff= 2 , 0
                          635.87         2051.78
Permanent Ineff=
       F       F
Bank Sta=560.7,593.2
XS Rating Curve= 0 ,0
Exp/Cntr=0.3,0.1

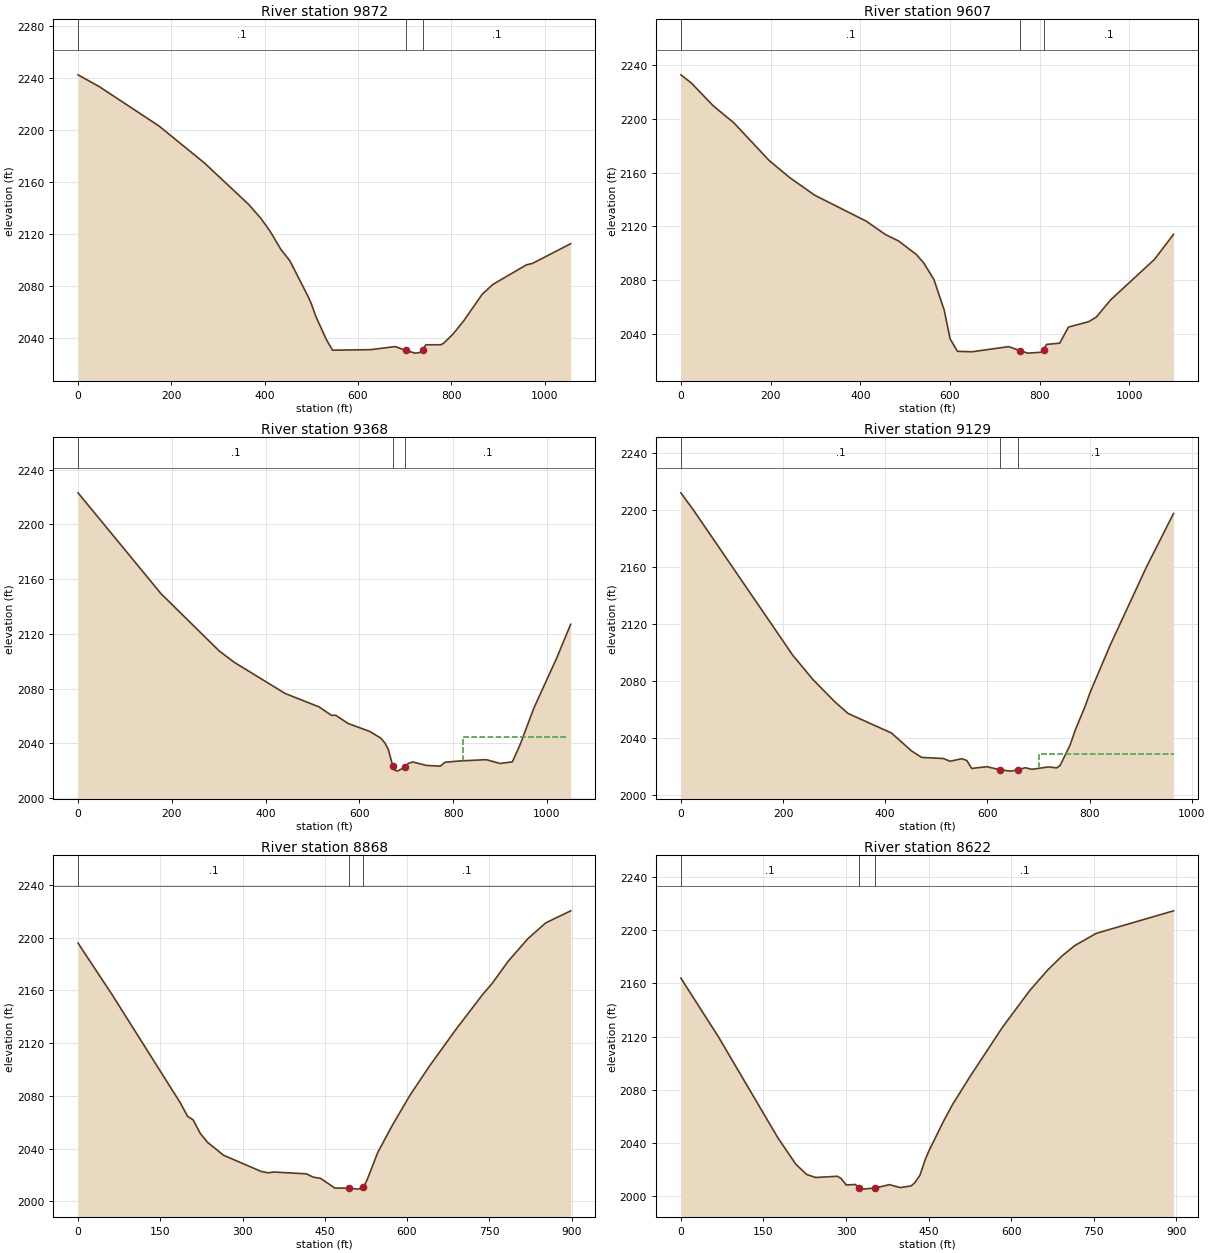
Type RM Length L Ch R = 1 ,9872    ,247.2,264.3,273
XS GIS Cut Line= 4
     2175915.138      238952.237     2175802.291      238445.293
     2175652.985      238263.001     2175352.638      238247.376
#Sta/Elev= 30
       0 2242.48    45.7 2233.37   173.1 2203.28   271.1  2174.7   365.8 2142.86
     392 2132.12   411.6 2122.28   434.4 2108.52     454 2099.57   493.2    2072
   499.8 2066.77   509.6 2056.88   532.4 2038.91   545.5 2030.93   627.4 2031.36
   679.7 2033.71   702.6 2030.71   722.3 2028.68   732.1 2029.07   738.6 2031.18
   745.2  2035.1   777.9 2035.11   784.4 2036.59     804 2043.48   826.9  2053.7
   866.1 2073.93     889 2081.47   960.9 2096.49     974 2097.63  1055.7 2112.75
#Mann= 3 ,-1 , 0
       0      .1       0   702.6    .045       0   738.6      .1       0
Bank Sta=702.6,738.6
XS Rating Curve= 0 ,0
Exp/Cntr=0.3,0.1

Type RM Length L Ch R = 1 ,9607    ,210,239,250.5
XS GIS Cut Line= 4
     2175934.235      238936.612     2175925.352      238333.263
     2175875.439      238114.079     2175774.513      237863.696
#Sta/Elev= 30
       0 2232.83      23 2226.84    72.2 2209.71   118.1 2197.08   196.8    2169
   242.7 2156.25   298.4 2143.13   413.2 2123.82   455.8  2113.9   485.4 2109.02
   524.7 2099.03   541.1 2092.83   564.1 2080.33     587 2057.56   600.1 2036.26
   616.4 2026.86     649 2026.52   730.5 2030.33   756.5 2027.31   772.8 2025.51
   802.2 2026.13   808.7 2027.83   815.2    2032   844.5 2032.93     864 2044.94
   909.5 2048.99   925.8 2052.28   958.3 2065.28  1055.9  2095.4  1098.2    2114
#Mann= 3 ,-1 , 0
       0      .1       0   756.5    .045       0   808.7      .1       0
Bank Sta=756.5,808.7
XS Rating Curve= 0 ,0
Exp/Cntr=0.3,0.1

Type RM Length L Ch R = 1 ,9368    ,228.8,239.9,251.5
XS GIS Cut Line= 3
     2175956.805      238927.932      2176074.86      238283.835
     2176220.694      237915.779
#Sta/Elev= 30
       0 2222.99   176.8 2149.36   301.2  2107.4     334 2098.96     442 2076.32
     514 2066.57   540.2 2060.47     550 2060.34   576.2  2054.4   622.1 2048.62
     645 2043.91   654.8 2040.07   661.4 2035.75   671.2 2023.51   674.5 2020.63
     681 2019.62   697.4 2022.51   703.9 2025.16   713.7 2026.34   743.2 2023.77
   772.6 2023.25   782.4 2026.07   815.2 2027.09   870.8 2027.99   900.2  2025.2
   926.4 2026.42   942.8 2038.94   972.2 2065.72  1021.3 2102.59  1050.7 2126.95
#Mann= 3 ,-1 , 0
       0      .1       0   671.2    .045       0   697.4      .1       0
#XS Ineff= 1 ,-1
  820.56 1040.82 2044.83
Permanent Ineff=
       F
Bank Sta=671.2,697.4
XS Rating Curve= 0 ,0
Exp/Cntr=0.3,0.1

Type RM Length L Ch R = 1 ,9129    ,252.3,260.2,264.7
XS GIS Cut Line= 3
     2175982.846      238929.668     2176215.485      238431.404
      2176543.27      238177.554
#Sta/Elev= 30
       0 2212.22    26.2 2199.29   219.3 2098.03   258.6 2081.06   301.1 2065.55
   327.3 2057.26   412.4 2043.49   451.7  2030.9   471.3 2026.38   513.9 2025.62
     527 2023.68   549.9 2025.47   559.7 2024.23   569.5 2018.64   598.9 2019.87
     625  2017.7   644.6 2016.75   660.9  2017.7     674 2019.15     687 2018.02
   719.6  2019.7     736 2019.04   742.5 2020.79   762.1 2035.15   771.9 2045.39
   791.5 2062.37   801.3  2072.1   840.4 2105.15   912.2 2160.64   964.5  2197.7
#Mann= 3 ,-1 , 0
       0      .1       0     625    .045       0   660.9      .1       0
#XS Ineff= 2 , 0
                          701.28         2028.76
Permanent Ineff=
       F       F
Bank Sta=625,660.9
XS Rating Curve= 0 ,0
Exp/Cntr=0.3,0.1

Type RM Length L Ch R = 1 ,8868    ,246.3,246.7,237.4
XS GIS Cut Line= 4
     2176015.833      238926.196     2176317.916      238625.849
     2176413.402      238584.182     2176649.613      238301.607
#Sta/Elev= 30
       0 2195.92    62.3  2156.7   186.8  2074.6   199.9 2064.45   209.7 2061.98
   222.8  2051.7   235.9 2044.93   265.4 2035.04   334.2 2022.72   347.3 2021.72
   357.2 2022.31   416.2 2020.96   429.2 2018.41   442.3 2017.52   468.3 2010.16
   494.4  2010.1   510.6 2009.34   520.4 2010.72   526.9 2016.03   546.5 2037.03
   572.5 2057.21   605.1 2080.35     641 2102.69   689.9 2130.86   738.8 2157.43
   755.1 2165.23   784.4  2182.1   820.2 2199.14   852.8 2211.23   898.5  2220.4
#Mann= 3 ,-1 , 0
       0      .1       0   494.4    .045       0   520.4      .1       0
Bank Sta=494.4,520.4
XS Rating Curve= 0 ,0
Exp/Cntr=0.3,0.1

Type RM Length L Ch R = 1 ,8622    ,266.8,252.2,225.8
XS GIS Cut Line= 3
     2176175.262      239017.684     2176529.721      238766.474
     2176687.998      238333.863
#Sta/Elev= 30
       0    2164    68.6 2119.54   176.4 2043.71   209.1 2023.81   228.7 2016.17
     245 2013.96   284.2 2014.86   290.7 2013.38   300.5 2008.33   316.9 2008.67
   323.9 2006.21   329.9 2005.19   352.8 2006.04   378.9 2008.56   398.5 2006.35
   418.1 2007.59   424.6  2009.8   434.4 2015.69   444.2 2027.68   450.8 2034.08
   476.9 2056.06   493.3 2068.65   525.9 2090.26   584.7 2127.24   633.7 2154.56
   666.4 2170.07   692.6 2180.69   715.4 2188.42   754.6 2197.67   895.1 2214.64
#Mann= 3 ,-1 , 0
       0      .1       0   323.9    .045       0   352.8      .1       0
Bank Sta=323.9,352.8
XS Rating Curve= 0 ,0
Exp/Cntr=0.3,0.1