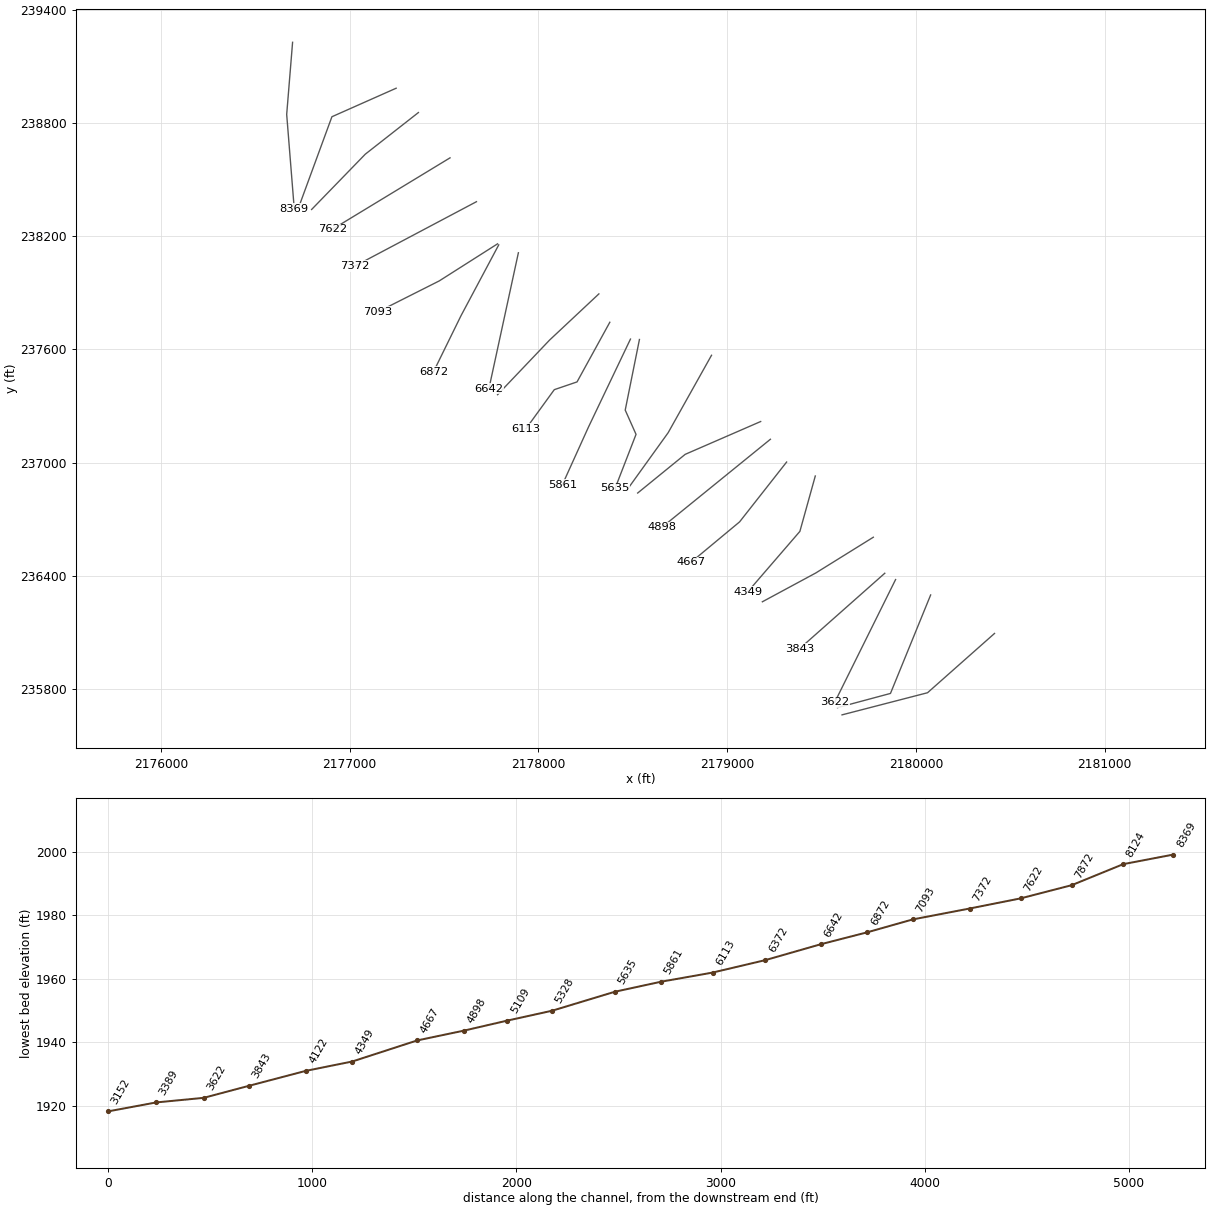
HEC-RAS study COVECK.prj: COVECK

--- COVECK.g01 (geometry) --- (continued)

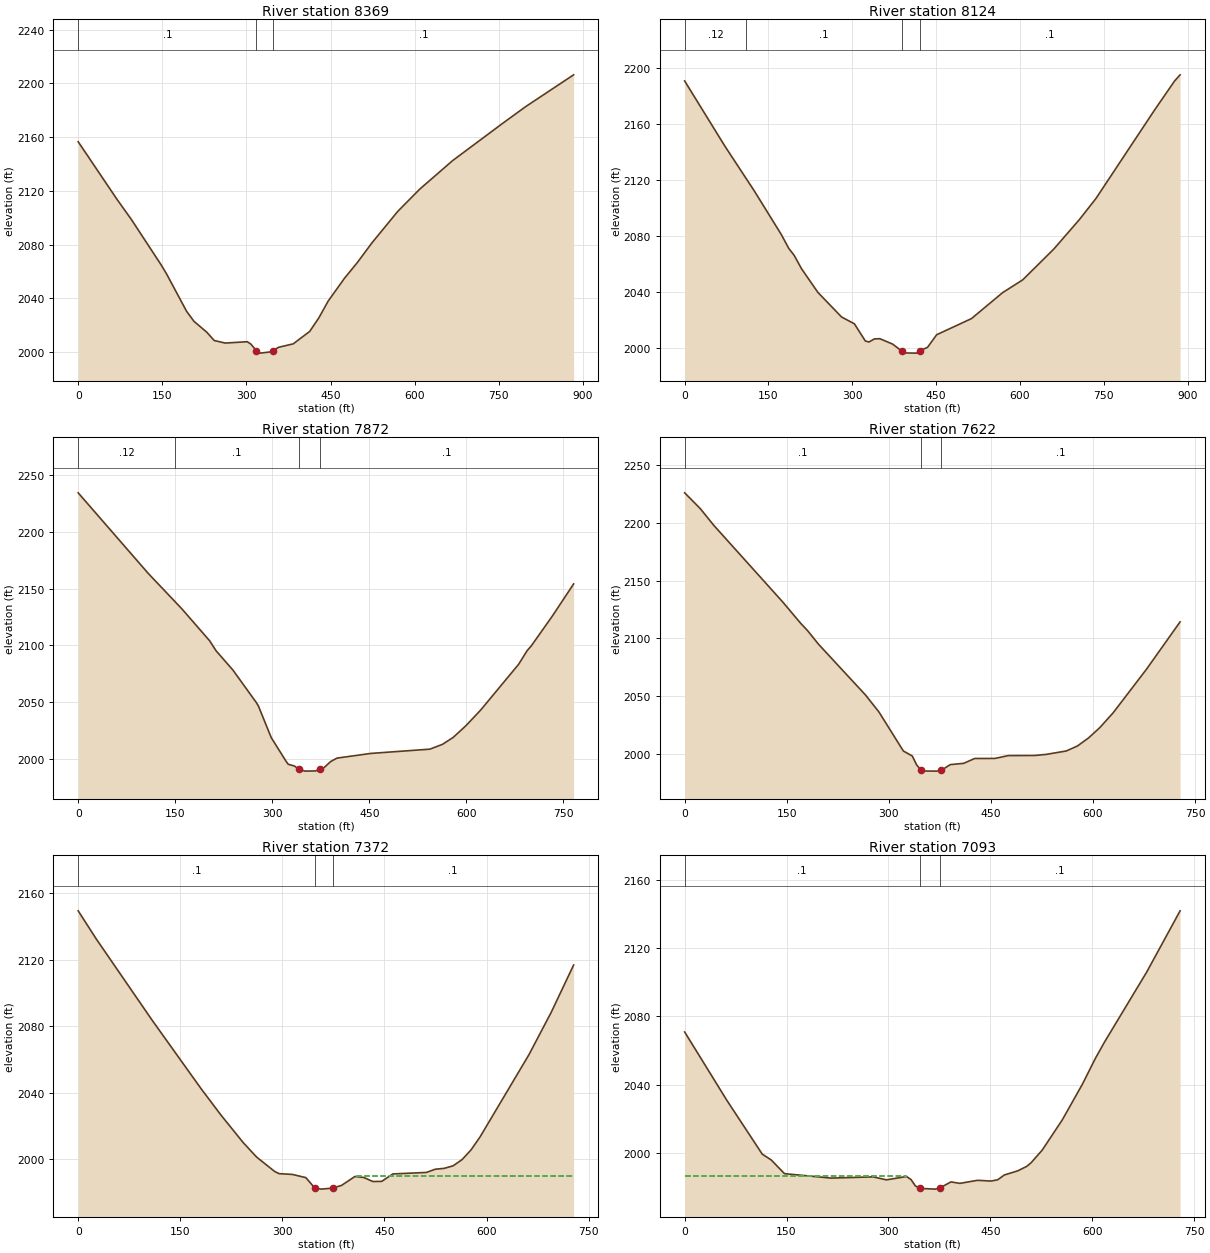
Type RM Length L Ch R = 1 ,8369    ,250,245.7,239.7
XS GIS Cut Line= 3
     2176698.106      239226.742     2176666.874      238844.599
     2176706.805      238346.335
#Sta/Elev= 30
       0  2156.6    68.8 2113.92      95 2098.57   147.5  2065.1   157.3 2058.32
   193.4 2030.16   206.5 2022.76   229.4 2014.63   242.5 2008.49   262.2 2006.58
   301.5 2007.58     308 2005.78   317.9 2000.73   324.4 1999.08   344.1 2000.06
   347.4  2000.9   357.2 2003.41   383.4    2006   412.8 2015.27   429.2 2025.45
   445.5 2037.74   474.9 2054.94   497.8 2066.64   523.9 2081.33   569.6 2104.63
   608.8 2121.22   667.6 2142.55   755.9 2170.04   798.3 2182.91   883.3 2206.46
#Mann= 3 ,-1 , 0
       0      .1       0   317.9    .045       0   347.4      .1       0
Bank Sta=317.9,347.4
XS Rating Curve= 0 ,0
Exp/Cntr=0.3,0.1

Type RM Length L Ch R = 1 ,8124    ,264.7,252.2,244.1
XS GIS Cut Line= 3
     2177246.735      238983.487     2176906.458      238832.446
     2176729.374      238349.807
#Sta/Elev= 30
       0 2190.94    71.8 2144.38   124.1 2112.52   173.1 2080.87   186.2  2071.1
   195.9 2066.09     209 2056.56   238.4 2039.54   280.8 2021.92   303.7 2017.04
   323.3 2004.74   329.8 2004.04   339.6 2006.27   349.4 2006.37   372.3 2002.48
   388.7 1997.43   395.2 1996.19   414.8 1996.06   421.4 1997.84   434.5  2000.2
   450.9 2009.23   513.1 2020.77   568.8 2039.34   604.8 2048.52   660.4 2070.54
   706.3 2091.71   735.8 2106.74   840.6 2170.04   876.6 2190.93   886.4 2195.32
#Mann= 4 ,-1 , 0
       0     .12       0     110      .1       0   388.7    .045       0
   421.4      .1       0
Bank Sta=388.7,421.4
XS Rating Curve= 0 ,0
Exp/Cntr=0.3,0.1

Type RM Length L Ch R = 1 ,7872    ,252.5,250,244.7
XS GIS Cut Line= 3
     2177364.712      238854.706     2177083.396      238634.217
     2176798.819      238341.126
#Sta/Elev= 30
       0 2234.14   108.2 2163.36   160.7 2131.86   203.3    2104   213.1  2095.3
   239.4 2078.17   275.4 2049.71   278.7  2046.6   298.4 2018.96   321.4 1998.07
   324.6 1995.51   334.5 1993.88     341 1991.07   350.9 1989.44   367.2 1989.62
   373.8 1991.29   380.3  1992.6   390.1 1997.78   399.9 2000.86   452.2    2005
   543.7 2008.76   563.3 2013.03   579.7 2019.08   599.3 2029.33   622.2 2043.13
     681 2083.46     694 2095.34   700.6 2099.68   733.3 2126.04   765.9 2154.03
#Mann= 4 ,-1 , 0
       0     .12       0     150      .1       0     341    .045       0
   373.8      .1       0
Bank Sta=341,373.8
XS Rating Curve= 0 ,0
Exp/Cntr=0.3,0.1

Type RM Length L Ch R = 1 ,7622    ,251.2,250,249.2
XS GIS Cut Line= 3
     2177532.197      238614.736     2177221.055      238425.827
     2176909.912      238236.918
#Sta/Elev= 30
       0 2225.94      23 2212.28    42.6 2197.97   144.3 2131.43   170.5 2113.11
   180.4 2106.92   196.8 2094.96   265.6 2051.22   285.3  2036.6   321.4 2002.67
   334.5 1998.36     341 1990.56   347.6 1986.03   350.9 1985.38   370.6 1985.28
   377.1 1985.93   390.2  1990.9   409.9    1992   426.3 1996.24   455.8 1996.25
   475.5 1998.72   514.8 1998.82   531.2 1999.75   560.8 2002.71   577.2 2007.03
   593.6 2014.05     610 2022.87   629.6 2035.69   678.8 2073.54     728 2114.36
#Mann= 3 ,-1 , 0
       0      .1       0   347.6    .045       0   377.1      .1       0
Bank Sta=347.6,377.1
XS Rating Curve= 0 ,0
Exp/Cntr=0.3,0.1

Type RM Length L Ch R = 1 ,7372    ,276.7,278.2,278.4
XS GIS Cut Line= 3
     2177672.149      238382.451      2177350.45      238212.139
     2177028.751      238041.828
#Sta/Elev= 30
       0 2149.47    26.2 2132.77   108.2 2083.95   180.4  2042.6   209.9 2026.58
   242.7 2009.96   262.3 2001.32   288.6 1992.74   295.1  1991.4   314.8 1990.92
   334.5    1989   347.6 1982.76   357.4 1982.08   373.8 1982.71     387 1984.33
   406.6 1989.67   419.8 1989.08   432.9 1986.65     446 1986.75   462.4 1991.22
   511.6 1992.11   524.7 1994.05   537.8 1994.57   550.9  1996.1     564 1999.81
   577.2 2005.66   590.3 2013.34   662.4 2062.98   695.2 2088.55     728 2116.88
#Mann= 3 ,-1 , 0
       0      .1       0   347.6    .045       0   373.8      .1       0
#XS Ineff= 2 , 0
                          409.92         1989.91
Permanent Ineff=
       F       F
Bank Sta=347.6,373.8
XS Rating Curve= 0 ,0
Exp/Cntr=0.3,0.1

Type RM Length L Ch R = 1 ,7093    ,209.9,221.8,230.5
XS GIS Cut Line= 3
     2177783.874      238159.211     2177475.146      237962.915
     2177150.405      237799.202
#Sta/Elev= 30
       0 2070.86    62.1 2030.78   114.3 1999.16   127.4  1995.8     147 1987.73
   215.6 1985.12   277.6 1985.84   297.2 1984.09   326.6 1986.05   333.2 1984.33
   339.7 1980.57   346.2 1979.09   369.1 1978.65   375.7 1979.32   392.1 1982.89
   405.2 1982.03   431.4 1983.83     451 1983.38   460.9 1984.12   470.7 1986.95
   490.4 1989.36   503.5 1991.96     510 1994.07   526.4  2001.5   555.9 2019.19
   585.4 2040.02     605 2055.53   618.1 2064.85   680.4 2106.05   729.5 2141.93
#Mann= 3 ,-1 , 0
       0      .1       0   346.2    .045       0   375.7      .1       0
#XS Ineff= 2 , 0
          326.47 1986.18
Permanent Ineff=
       F       F
Bank Sta=346.2,375.7
XS Rating Curve= 0 ,0
Exp/Cntr=0.3,0.1

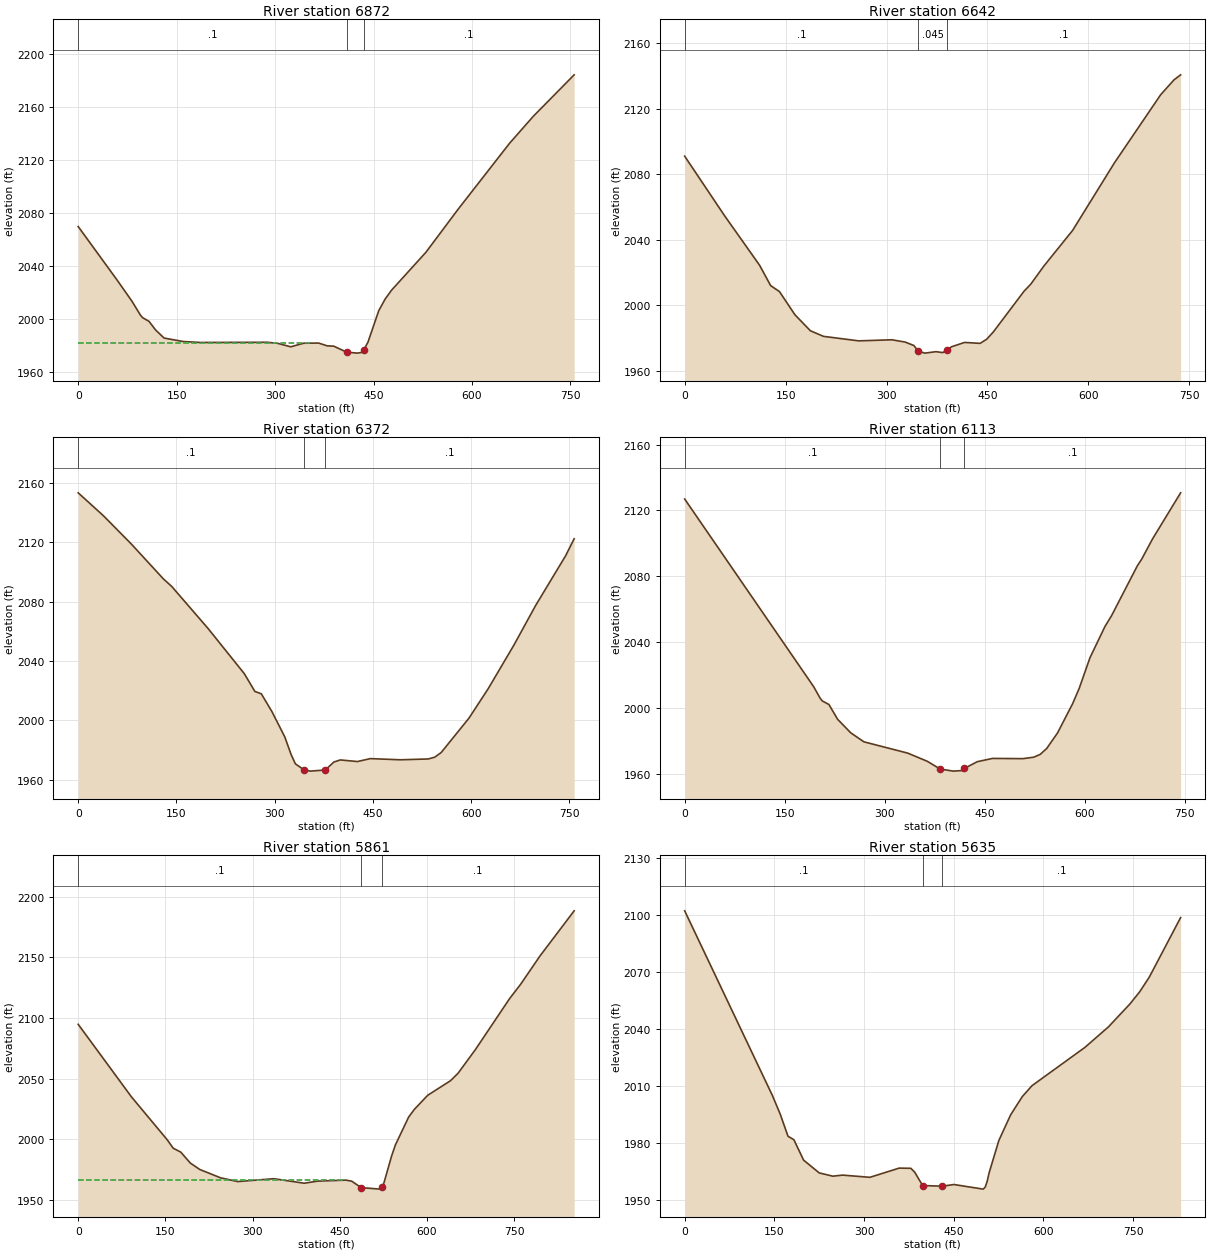
Type RM Length L Ch R = 1 ,6872    ,223.5,229.7,231.1
XS GIS Cut Line= 3
     2177790.138      238153.626     2177590.266      237778.416
     2177444.652      237481.751
#Sta/Elev= 30
       0 2070.12    58.9    2030    81.8 2013.86    94.8 2003.31    98.1 2001.38
   107.9 1998.57   117.7  1992.2   130.8 1985.99   160.2 1983.35   186.4 1982.66
   287.8  1982.8   304.1 1981.98   323.8 1979.38   343.4 1982.08   366.3 1982.21
   379.3  1980.1   389.2 1979.89   408.8  1975.4   425.1 1974.61   431.7  1975.1
   434.9 1976.84   441.5 1982.94   457.8 2006.54   467.7 2015.47   477.5 2022.18
   529.8 2050.74   578.9 2083.26   657.4  2133.1   693.4 2153.35   755.6 2184.64
#Mann= 3 ,-1 , 0
       0      .1       0   408.8    .045       0   434.9      .1       0
#XS Ineff= 2 , 0
          356.36 1982.54
Permanent Ineff=
       F       F
Bank Sta=408.8,434.9
XS Rating Curve= 0 ,0
Exp/Cntr=0.3,0.1

Type RM Length L Ch R = 1 ,6642    ,281.4,270.3,255
XS GIS Cut Line= 2
     2177894.305       238111.96     2177738.055      237391.474
#Sta/Elev= 30
       0 2090.97      59 2054.82   111.4  2024.4   127.8    2012   140.9 2008.37
   163.8 1994.27   186.8 1984.47   206.4 1981.04   258.8 1978.29     308 1978.95
   327.7 1977.57   340.8 1975.42   347.3 1971.91   357.2 1970.81   373.5  1971.7
   383.4 1971.14   389.9 1972.46   396.5 1974.67   416.1 1977.34   439.1 1976.76
   448.9 1979.28   458.7 1983.67   504.6 2008.65   514.4 2012.85   534.1 2024.03
   576.7  2045.7   638.9 2086.95   707.7 2128.55   727.4 2137.54   737.2  2140.6
#Mann= 3 ,-1 , 0
       0      .1       0   347.3    .045       0   389.9      .1       0
Bank Sta=347.3,389.9
XS Rating Curve= 0 ,0
Exp/Cntr=0.3,0.1

Type RM Length L Ch R = 1 ,6372    ,266.7,258.5,246.9
XS GIS Cut Line= 3
     2178320.716      237894.094      2178059.69      237649.617
     2177784.055      237360.239
#Sta/Elev= 30
       0 2153.48      39 2137.82    81.3 2118.88     130 2095.48     143 2090.27
   198.3    2062   253.6 2031.57   269.8 2019.55   279.6 2017.97   295.9  2005.9
   315.4 1988.94   325.1 1977.03   331.6 1970.75   344.6 1966.78   354.4 1965.83
   377.3 1966.61   390.4 1971.96   400.2 1973.38   426.4 1972.29   446.1 1974.27
   491.9 1973.48   534.5 1974.03   544.4 1975.24   554.2 1978.34   596.8 2001.62
   626.2 2021.51   665.6 2051.03   698.3 2077.38   744.2 2110.99   757.3  2122.5
#Mann= 3 ,-1 , 0
       0      .1       0   344.6    .045       0   377.3      .1       0
Bank Sta=344.6,377.3
XS Rating Curve= 0 ,0
Exp/Cntr=0.3,0.1

Type RM Length L Ch R = 1 ,6113    ,224.1,251.6,262.1
XS GIS Cut Line= 4
      2178378.68      237743.904     2178205.069      237427.932
     2178084.525      237386.851     2177934.235      237179.668
#Sta/Elev= 30
       0 2126.93   193.4 2013.15   203.2  2006.1   206.5 2004.44   216.3 2002.33
   229.4 1993.33   249.1 1985.12   268.8 1979.67   334.3 1972.85   363.8 1967.88
   383.4 1963.12     403  1961.9     416 1962.25   419.3 1963.52   438.9 1967.63
   461.8 1969.61   507.3 1969.47   523.5 1970.35   533.2 1972.04     543 1975.66
   559.2 1985.05   581.8 2002.77   591.6 2011.98   607.8 2030.63   630.4 2049.67
   640.2 2056.15     679  2086.5   685.5 2090.51   701.7 2102.74   743.8 2130.69
#Mann= 3 ,-1 , 0
       0      .1       0   383.4    .045       0   419.3      .1       0
Bank Sta=383.4,419.3
XS Rating Curve= 0 ,0
Exp/Cntr=0.3,0.1

Type RM Length L Ch R = 1 ,5861    ,199.2,227,238.5
XS GIS Cut Line= 3
     2178488.041      237654.717     2178265.581      237188.715
     2178126.501      236881.758
#Sta/Elev= 30
       0 2094.84    91.5 2035.12   153.6 1999.44   163.4 1992.77   176.5 1989.53
   192.8 1980.58   209.2 1975.22   245.1 1968.33   274.5 1965.25   336.6 1967.62
   388.9 1963.89   411.8 1965.61   460.8 1966.45   470.6 1965.58     487 1960.26
   519.6 1959.03   522.9 1960.68   526.2 1964.35   539.3 1986.37   545.8 1995.44
   568.7 2018.49   578.5 2024.79   601.4 2036.36   640.7 2048.39   653.8 2054.62
   683.2 2073.81   742.1 2115.86   761.8 2128.17   794.5  2151.1   853.4 2188.36
#Mann= 3 ,-1 , 0
       0      .1       0     487    .045       0   522.9      .1       0
#XS Ineff= 2 , 0
          457.67 1966.56
Permanent Ineff=
       F       F
Bank Sta=487,522.9
XS Rating Curve= 0 ,0
Exp/Cntr=0.3,0.1

Type RM Length L Ch R = 1 ,5635    ,321.8,306.6,292.2
XS GIS Cut Line= 4
     2178535.603      237652.633     2178460.277      237278.626
     2178517.569      237150.154     2178406.458      236863.696
#Sta/Elev= 30
       0 2102.01   146.7 2005.03   159.8 1995.24   172.8 1983.62   182.6 1981.82
   198.9 1971.08     225 1964.38   247.8 1962.66   264.1 1963.22   309.8 1962.06
   358.7  1966.9   378.3 1966.79   384.8 1964.72   397.9 1957.76   430.6 1957.39
   450.2 1958.28   499.3 1955.86   502.6 1956.92   505.8 1959.83   509.1 1964.38
   525.4 1981.39   545.1 1994.85   564.7 2004.48     581 2010.22   669.3 2030.28
   708.5 2041.01   744.4 2053.02   760.8 2059.42   777.1 2067.24   829.4 2098.47
#Mann= 3 ,-1 , 0
       0      .1       0   397.9    .045       0   430.6      .1       0
Bank Sta=397.9,430.6
XS Rating Curve= 0 ,0
Exp/Cntr=0.3,0.1

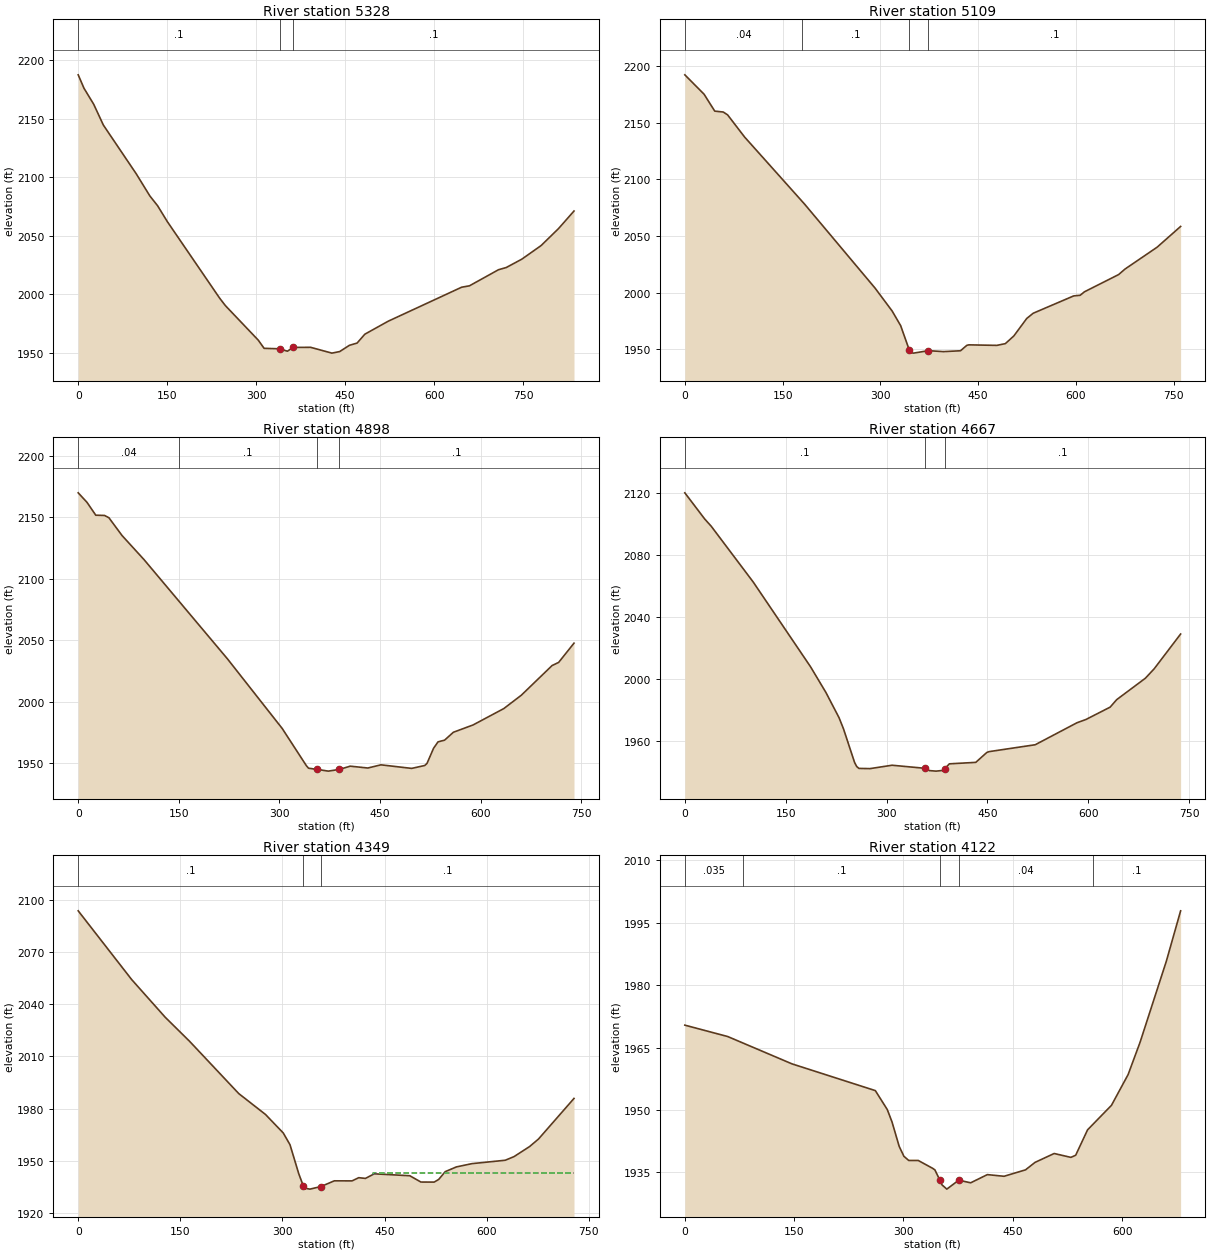
Type RM Length L Ch R = 1 ,5328    ,230.5,219.3,208.5
XS GIS Cut Line= 3
     2178917.475      237569.022     2178687.708      237158.835
     2178474.166       236861.96
#Sta/Elev= 30
       0 2187.36     9.8 2175.86    26.1 2162.27    42.4  2144.5      98 2102.78
   120.8    2084   133.9 2075.62   150.2 2062.14   238.3  1996.9   248.1 1990.44
   303.6 1960.93   313.4 1953.98   339.6 1953.58   352.6 1951.53   362.4 1954.76
   391.8 1954.84   427.7 1949.89   440.8 1951.23   457.1 1956.53   470.2 1958.49
   483.2 1966.04   522.4 1977.07   646.5 2006.16   659.5  2007.3   708.5 2021.05
   721.6 2022.94   747.7 2030.02   780.4 2041.69   809.7 2056.15   835.8 2071.15
#Mann= 3 ,-1 , 0
       0      .1       0   339.6    .045       0   362.4      .1       0
Bank Sta=339.6,362.4
XS Rating Curve= 0 ,0
Exp/Cntr=0.3,0.1

Type RM Length L Ch R = 1 ,5109    ,204,210.4,215.5
XS GIS Cut Line= 3
     2179177.822      237218.094     2178777.985      237044.251
     2178526.249       236839.39
#Sta/Elev= 30
       0 2192.05    29.5 2174.98    45.9 2160.07      59 2159.26    65.6 2156.78
    91.8 2137.16   183.6 2078.18   291.8 2004.11     318 1983.93   331.1 1971.02
   344.2 1949.75   347.5 1947.16   350.8 1946.78   373.7 1948.95   396.7 1948.11
   422.9 1948.86   432.7 1953.68     436 1954.07   478.6 1953.61   491.7 1955.14
   504.8 1961.96   524.5  1977.3   534.4 1981.92   596.6 1997.22   606.5 1997.76
     613 2000.81   665.5 2016.01   675.3 2020.87   724.5 2040.12   760.6 2058.43
#Mann= 4 ,-1 , 0
       0     .04       0     180      .1       0   344.2    .045       0
   373.7      .1       0
Bank Sta=344.2,373.7
XS Rating Curve= 0 ,0
Exp/Cntr=0.3,0.1

Type RM Length L Ch R = 1 ,4898    ,226.1,230.9,234.9
XS GIS Cut Line= 2
     2179229.374      237124.112      2178655.21      236658.201
#Sta/Elev= 30
       0 2169.78    13.1 2162.07    26.2  2151.6    39.3  2151.4    45.8 2149.54
    65.4 2135.07    98.2 2115.49   222.5 2034.92   304.3 1978.26   340.3 1948.05
   343.5 1946.03   356.6 1945.03     373 1943.65   389.3 1945.01   405.7 1947.68
   431.9 1946.18   451.5 1948.76   497.3 1945.87   516.9 1948.24   520.2 1949.95
     530 1962.25   536.6 1967.42   546.4 1968.82   559.5 1975.23   588.9 1981.17
   634.7 1994.47   660.9 2005.35   706.7 2029.44   716.5 2031.98   739.4 2047.63
#Mann= 4 ,-1 , 0
       0     .04       0     150      .1       0   356.6    .045       0
   389.3      .1       0
Bank Sta=356.6,389.3
XS Rating Curve= 0 ,0
Exp/Cntr=0.3,0.1

Type RM Length L Ch R = 1 ,4667    ,312.3,318.1,310.8
XS GIS Cut Line= 3
     2179315.316      237003.511      2179066.18      236686.612
     2178809.235      236473.071
#Sta/Elev= 30
       0 2120.41    29.5 2103.53    39.3 2098.78   101.6 2062.81   186.8 2008.07
   209.8 1991.36   229.4 1974.99     236 1967.76   252.4 1946.15   255.6  1943.5
   258.9 1942.29   275.3 1942.15   308.1 1944.34   357.2 1942.35   363.8 1940.87
   373.6 1940.53   383.4 1940.98   386.7 1942.18   393.3 1945.24   432.6 1946.19
     449 1952.58   452.2 1953.12     521 1957.58   583.2 1971.82   596.4  1973.9
   632.4 1981.89   642.2 1986.75   684.8 2000.58   697.9 2006.68   737.2 2029.15
#Mann= 3 ,-1 , 0
       0      .1       0   357.2    .045       0   386.7      .1       0
Bank Sta=357.2,386.7
XS Rating Curve= 0 ,0
Exp/Cntr=0.3,0.1

Type RM Length L Ch R = 1 ,4349    ,231.6,227.6,217.4
XS GIS Cut Line= 3
     2179467.221      236929.668     2179385.624      236636.265
     2179108.729      236315.468
#Sta/Elev= 30
       0 2093.55    78.6 2054.09   127.7 2032.54   163.7 2018.66   235.8 1988.72
   275.1 1976.73   301.3 1966.06   311.1 1959.38   324.1 1942.58   330.6 1935.82
   333.7 1934.37   340.4 1933.89   356.7 1935.39   376.2 1938.65   402.3 1938.62
   412.1 1940.45   421.9 1940.04   434.9 1942.67   487.1 1941.57   503.4 1937.96
   522.9 1937.92   529.5 1939.44   539.2 1943.93   555.5 1946.63   578.4 1948.51
   627.3 1950.46   640.3 1952.56   663.1 1958.32   676.2 1962.65   728.3 1985.92
#Mann= 3 ,-1 , 0
       0      .1       0   330.6    .045       0   356.7      .1       0
#XS Ineff= 2 , 0
                          432.79         1942.96
Permanent Ineff=
       F       F
Bank Sta=330.6,356.7
XS Rating Curve= 0 ,0
Exp/Cntr=0.3,0.1

Type RM Length L Ch R = 1 ,4122    ,271.8,279,279.3
XS GIS Cut Line= 3
      2179774.65       236605.28     2179469.288      236415.616
     2179186.854      236263.385
#Sta/Elev= 30
       0 1970.39    58.8 1967.65   147.1 1961.07   261.4 1954.64   277.8 1950.08
   284.3  1947.1   294.1 1941.24   300.6 1938.84   307.2 1937.84   320.2 1937.84
   339.9 1935.96   343.1 1935.58   349.7 1933.19   352.9 1931.96   359.5 1930.94
   375.8 1933.09   392.2 1932.46   415.1 1934.43     438 1934.03   467.5 1935.58
   480.6 1937.38   506.8 1939.51   529.7 1938.58   536.3 1939.09   552.6  1945.2
   585.4  1951.1   608.3 1958.52   624.7 1966.29   660.7 1985.77   680.3 1997.89
#Mann= 5 ,-1 , 0
       0    .035       0      80      .1       0   349.7    .045       0
   375.8     .04       0  559.47      .1       0
Bank Sta=349.7,375.8
XS Rating Curve= 0 ,0
Exp/Cntr=0.3,0.1

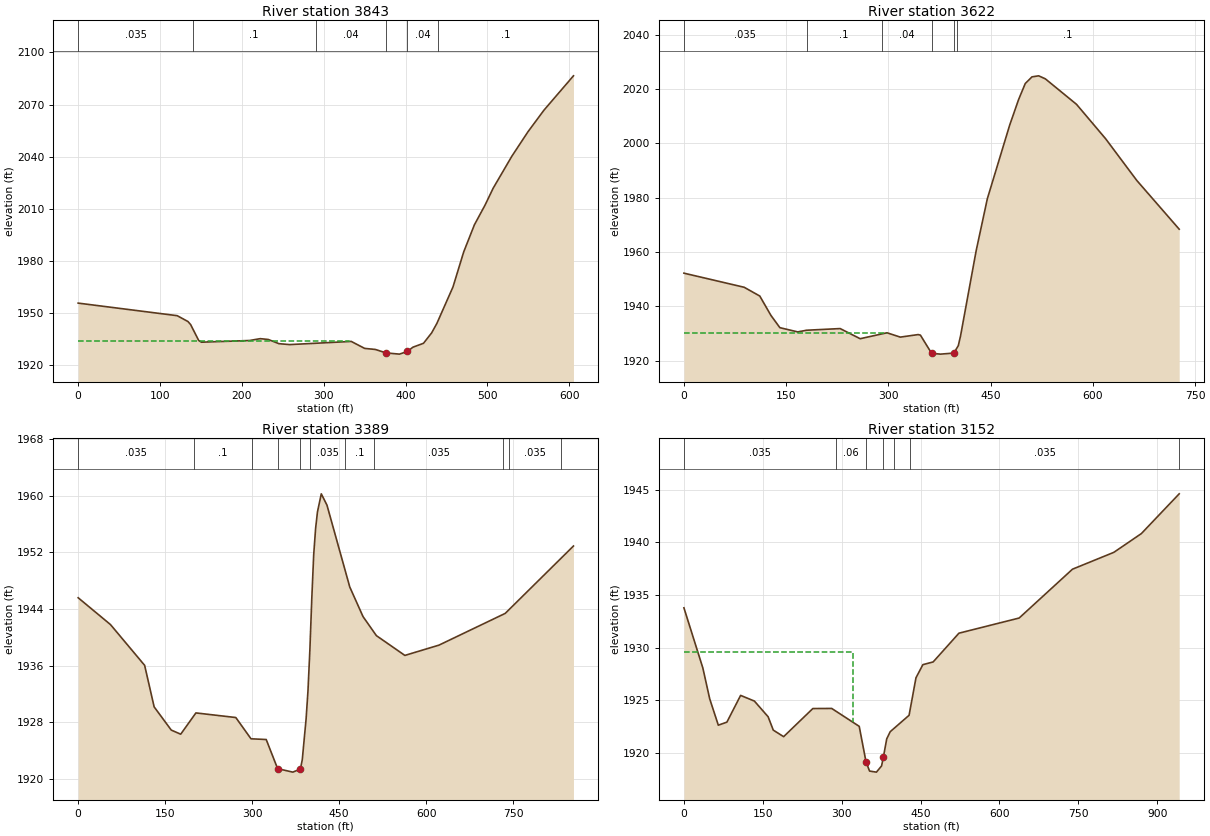
Type RM Length L Ch R = 1 ,3843    ,211.4,220.9,226.1
XS GIS Cut Line= 2
     2179835.291      236414.426     2179382.166      236013.385
#Sta/Elev= 30
       0 1955.61     121 1948.36   134.1 1945.01   137.4 1943.23   147.2 1934.12
   150.5 1933.09   209.3 1934.06   222.4 1935.13   232.2 1934.66   245.3 1932.24
   258.4 1931.71   333.6 1933.54     350 1929.52   363.1 1928.91   376.2 1926.91
   392.5 1926.22   402.3 1927.78   408.9  1930.2   421.9 1932.47   431.8 1938.43
   438.3 1943.98   457.9 1964.91     471  1985.1   484.1 2000.74   497.2 2012.17
     507  2021.8   529.9 2040.28   549.5  2054.3   569.1 2066.78   605.1 2086.54
#Mann= 6 ,-1 , 0
       0    .035       0     140      .1       0     290     .04       0
   376.2    .045       0   402.3     .04       0     440      .1       0
#XS Ineff= 2 , 0
          330.35 1933.59
Permanent Ineff=
       F       F
Bank Sta=376.2,402.3
XS Rating Curve= 0 ,0
Exp/Cntr=0.3,0.1

Type RM Length L Ch R = 1 ,3622    ,229.5,232.3,232.5
XS GIS Cut Line= 2
     2179892.569      236381.057     2179569.652      235730.015
#Sta/Elev= 30
       0 1952.22    88.4 1947.03   111.3 1943.81   127.7 1936.67   140.8 1932.17
     167 1930.61     180 1931.23   229.2 1931.84   258.6 1928.11   297.9 1930.29
   317.5  1928.7   343.7 1929.63     347 1929.42   363.4 1922.74   376.5 1922.44
   396.1 1922.83   402.6 1925.56   405.9 1929.17   428.8  1960.5   445.2  1979.6
   477.9 2006.62     491 2016.04   500.8 2021.96   510.7 2024.42   520.5  2024.8
   530.3 2023.69   576.1  2014.3   618.7 2001.67   664.5 1986.31   726.7 1968.39
#Mann= 6 ,-1 , 0
       0    .035       0     180      .1       0     290     .04       0
   363.4    .045       0   396.1     .04       0     400      .1       0
#XS Ineff= 2 , 0
          298.05 1930.28
Permanent Ineff=
       F       F
Bank Sta=363.4,396.1
XS Rating Curve= 0 ,0
Exp/Cntr=0.3,0.1

Type RM Length L Ch R = 1 ,3389    ,243.4,237.2,223.1
XS GIS Cut Line= 3
     2180078.333       236299.46     2179865.475      235777.958
      2179584.64      235702.621
#Sta/Elev= 30
       0 1945.59    55.7 1941.81   114.6 1936.06     131  1930.2   160.5 1926.93
   176.8 1926.35     203 1929.35   271.8  1928.7     298  1925.7   324.2  1925.6
   343.9 1921.49   370.1    1921   383.2 1921.44   386.4 1922.75     393 1928.51
   396.2 1932.42   399.5 1938.22   402.8 1945.46   406.1 1951.66   409.4 1955.38
   412.6  1957.7   419.2 1960.25     429 1958.65   468.3 1947.11   491.2 1942.93
   514.2 1940.25   563.3 1937.46   622.1 1938.91   736.4 1943.39     854 1952.89
#Mann= 11 ,-1 , 0
       0    .035       0     200      .1       0     300     .04       0
   343.9    .045       0   383.2     .04       0     400    .035       0
     460      .1       0     510    .035       0  733.27      .1       0
  743.27    .035       0  833.27      .1       0
Bank Sta=343.9,383.2
XS Rating Curve= 0 ,0
Exp/Cntr=0.3,0.1

Type RM Length L Ch R = 1 ,3152    ,448.8,471.7,468.9
XS GIS Cut Line= 3
     2180416.694      236095.676     2180061.854      235781.614
     2179608.946      235664.426
#Sta/Elev= 30
       0 1933.77      36 1928.05      49 1925.13    65.4 1922.62    81.7 1922.91
   107.8 1925.45     134 1924.91   160.1 1923.42   169.9 1922.15   189.6 1921.53
   245.1  1924.2     281 1924.21   333.3 1922.51   346.3 1919.12     353 1918.26
     366 1918.16   375.8 1918.75   379.1 1919.55   385.6 1921.32   392.2    1922
   428.1 1923.56   441.2 1927.12   454.3 1928.37   473.9 1928.63   522.9 1931.36
   637.4  1932.8   738.8 1937.44   817.4 1939.04   869.7 1940.82   941.7  1944.6
#Mann= 7 ,-1 , 0
       0    .035       0     290     .06       0   346.3    .045       0
   379.1     .06       0     400     .04       0     430    .035       0
  941.69      .1       0
#XS Ineff= 2 , 0
          321.56 1929.58
Permanent Ineff=
       F       F
Bank Sta=346.3,379.1
XS Rating Curve= 0 ,0
Exp/Cntr=0.3,0.1