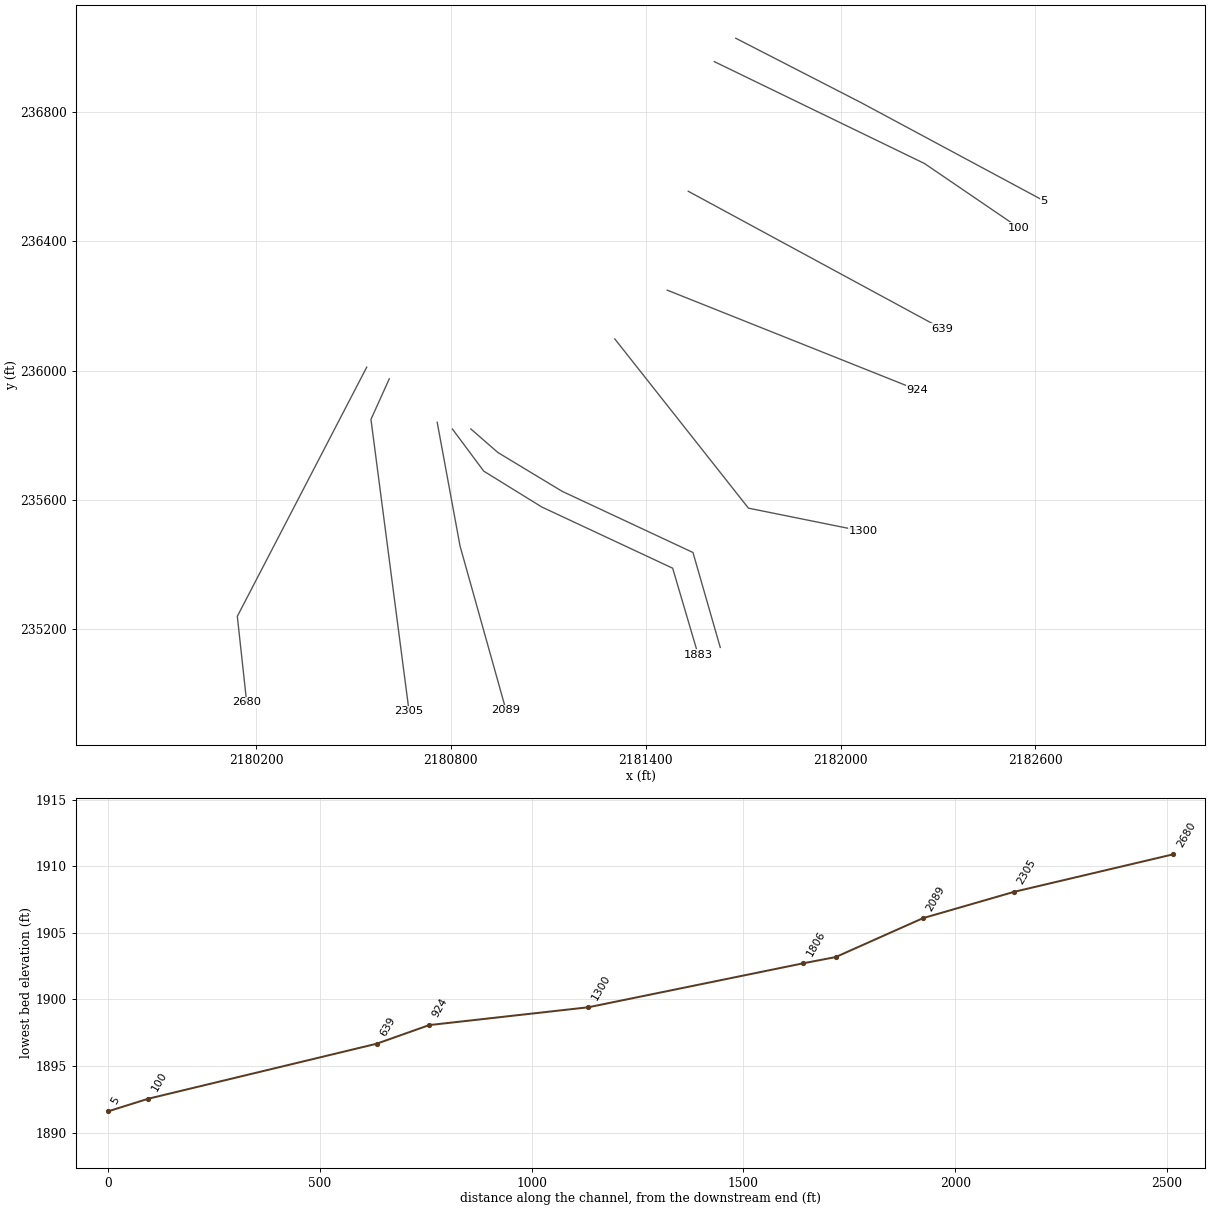
HEC-RAS study COVECK.prj: COVECK

--- COVECK.g01 (geometry) --- (continued)

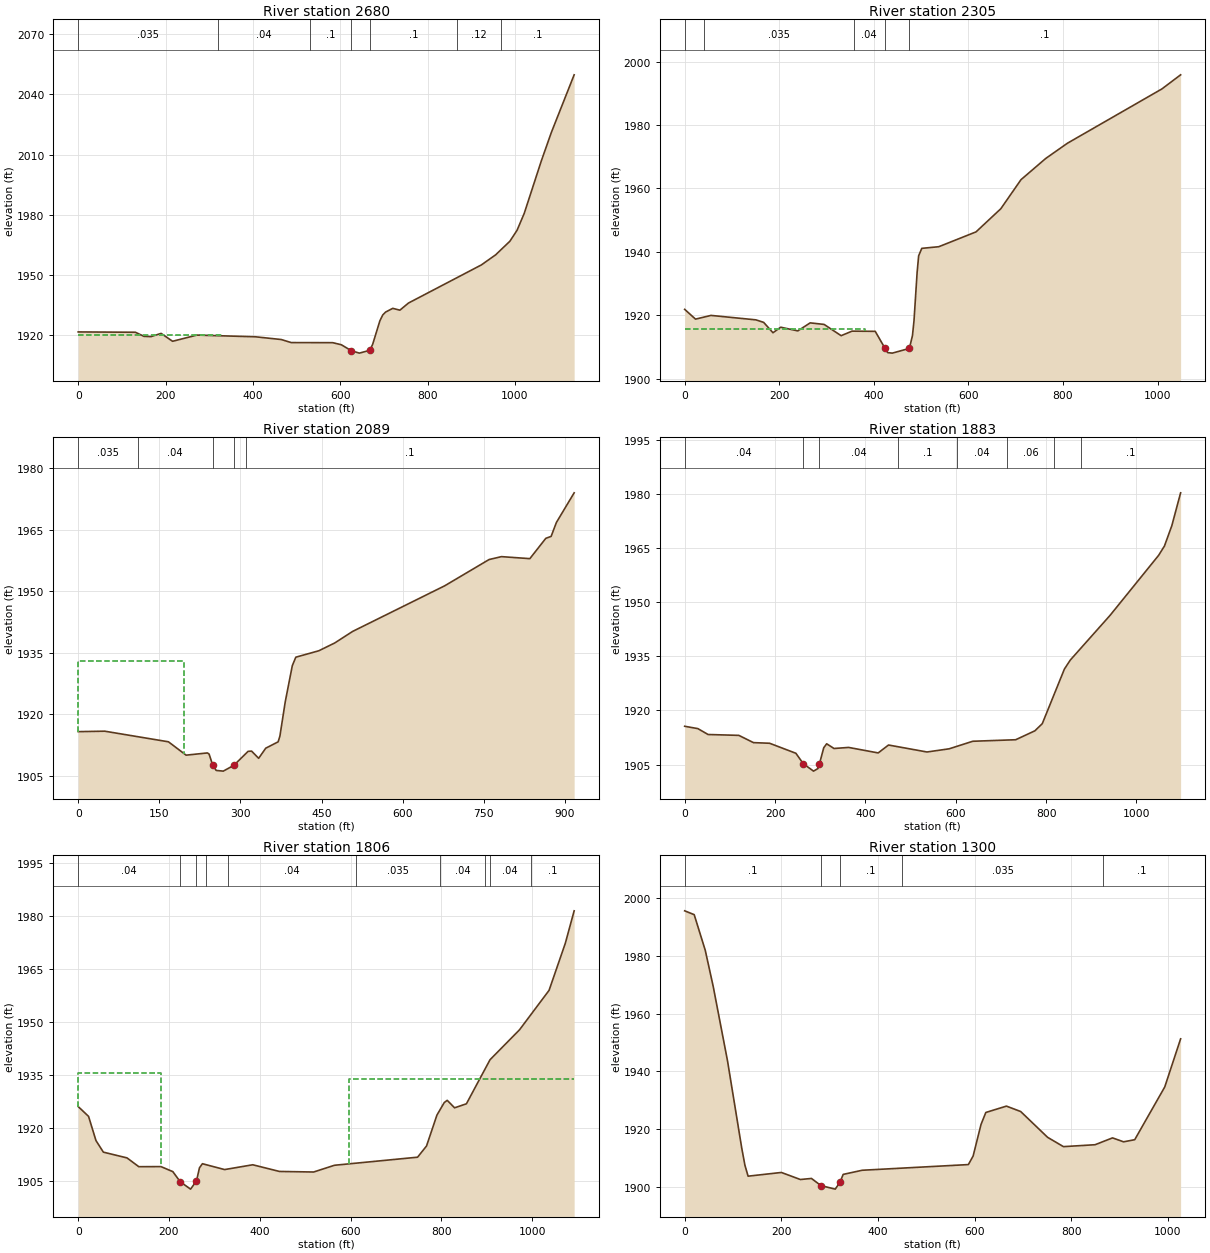
Type RM Length L Ch R = 1 ,2680    ,356.5,375.8,384.3
XS GIS Cut Line= 3
     2180541.021      236010.781     2180142.583      235239.947
     2180171.446      234973.454
#Sta/Elev= 30
       0 1921.48     131 1921.32   150.6 1919.27     167 1919.15   189.9 1920.75
   216.1 1916.81   271.8  1919.9     406 1919.05     465 1917.69   487.9 1916.16
   582.8 1916.12   602.5 1915.09   625.4 1912.13   643.8  1910.9     668 1912.32
   674.5 1915.39   690.9 1927.04   697.4 1929.93     704 1931.39   720.4 1933.25
   736.7 1932.34   756.4  1935.9   923.3 1954.92     956 1959.96   988.7 1966.76
    1005 1972.21  1021.4  1980.6  1060.6 2006.83  1083.5    2021  1135.8  2049.8
#Mann= 7 ,-1 , 0
       0    .035       0     320     .04       0     530      .1       0
   625.4    .045       0     668      .1       0  867.72     .12       0
  967.72      .1       0
#XS Ineff= 2 , 0
          330.41 1919.89
Permanent Ineff=
       F       F
Bank Sta=625.4,668
XS Rating Curve= 0 ,0
Exp/Cntr=0.3,0.1

Type RM Length L Ch R = 1 ,2305    ,214,215.5,217.3
XS GIS Cut Line= 3
     2180610.465      235974.756     2180554.041      235849.322
     2180671.446      234945.676
#Sta/Elev= 30
       0 1921.88    22.9  1918.8    55.7 1919.97   150.6 1918.57     167 1917.78
   186.7 1914.51   203.1 1916.25   239.2 1915.09   265.4 1917.62   294.9 1917.13
   330.9 1913.58   353.9 1915.01     403 1914.95   422.7 1909.84   429.3 1908.24
   439.1 1908.08   475.2 1909.57   481.7 1913.59     485 1918.36   491.6  1933.6
   494.8 1938.75   501.4 1941.11   537.4 1941.63   616.1  1946.3   668.6 1953.61
   711.2 1962.76   763.6 1969.46   809.5 1974.26  1009.4 1991.39  1048.8 1995.82
#Mann= 5 ,-1 , 0
       0     .04       0      40    .035       0  357.54     .04       0
   422.7    .045       0   475.2      .1       0
#XS Ineff= 2 , 0
          381.34 1915.69
Permanent Ineff=
       F       F
Bank Sta=422.7,475.2
XS Rating Curve= 0 ,0
Exp/Cntr=0.3,0.1

Type RM Length L Ch R = 1 ,2089    ,185.6,205.9,222.6
XS GIS Cut Line= 3
      2180758.02      235840.258     2180828.333      235457.446
     2180970.057      234949.149
#Sta/Elev= 30
       0 1915.74    49.1 1915.85   166.8 1913.26   199.5    1910   238.8 1910.54
     242 1910.26   248.6 1907.59   255.1 1906.27   268.2  1906.1   287.8 1907.52
     314 1910.92   320.5 1910.99   333.6 1909.23   346.7  1911.7   369.6 1913.25
   372.9 1914.65   382.7 1922.98   395.8 1931.84   402.3 1933.92   444.9 1935.49
   474.4  1937.4   507.2  1940.2   677.6 1951.35   759.6 1957.76   782.5 1958.47
     835 1957.98   864.5 1962.94   874.3 1963.41   884.1 1966.82   916.9 1974.05
#Mann= 5 ,-1 , 0
       0    .035       0     110     .04       0   248.6    .045       0
   287.8     .04       0     310      .1       0
#XS Ineff= 2 , 0
          195.46 1932.96
Permanent Ineff=
       F       F
Bank Sta=248.6,287.8
XS Rating Curve= 0 ,0
Exp/Cntr=0.5,0.3

Type RM Length L Ch R = 1 ,1883    ,76.9,76.8,76.9
XS GIS Cut Line= 5
     2180804.895      235819.425     2180901.249      235689.217
     2181080.242      235578.106      2181483.02      235388.869
     2181561.854      235120.156
#Sta/Elev= 30
       0  1915.6    29.2 1914.95    51.8 1913.32   119.9 1913.08   152.3 1911.07
   187.9  1910.9   246.2 1908.12   262.5 1905.23   285.2 1903.18   294.9 1903.89
   298.1  1905.1   307.8 1909.65   314.3 1910.75   330.5 1909.45   362.9 1909.74
   428.3 1908.22   451.2 1910.41   536.3 1908.48   585.4 1909.36   637.7 1911.45
   732.6 1911.87   775.1 1914.34   791.5 1916.32   840.5 1931.45   853.5 1933.93
   941.4 1946.29  1048.9 1962.91  1061.9 1965.51  1078.2 1971.13  1097.7 1980.24
#Mann= 8 ,-1 , 0
       0     .04       0   262.5    .045       0   298.1     .04       0
  472.66      .1       0  602.66     .04       0  712.66     .06       0
  817.68     .04       0  877.68      .1       0
Bank Sta=262.5,298.1
XS Rating Curve= 0 ,0
Exp/Cntr=0.5,0.3

Type RM Length L Ch R = 1 ,1806    ,510.6,506.9,495.7
XS GIS Cut Line= 5
     2180861.608      235819.656     2180944.941       235746.74
     2181142.742      235626.717      2181545.52      235437.481
     2181629.562      235143.593
#Sta/Elev= 30
       0  1926.1    22.8 1923.33    39.1 1916.48    55.4 1913.19   107.5 1911.56
   133.5 1909.07   182.4 1909.09   208.5 1907.67   224.8 1904.79   247.6 1902.71
   260.6 1905.02   267.2 1908.75   273.7 1909.91   322.6 1908.25   384.6 1909.61
   443.5 1907.72   518.8 1907.56   564.6 1909.47   747.8 1911.76   767.5 1914.93
   790.4 1923.68   806.6 1927.25   813.1 1927.87   829.4 1925.75   855.4 1926.89
   907.4 1939.37   972.5 1947.87  1037.5 1959.03  1073.3 1972.36  1092.8 1981.57
#Mann= 10 ,-1 , 0
       0     .04       0   224.8    .045       0   260.6     .04       0
  280.73      .1       0  330.73     .04       0   612.1    .035       0
  797.11     .04       0  897.11      .1       0  907.11     .04       0
  997.11      .1       0
#XS Ineff= 2 , 0
           183.1 1935.59  597.73          1933.8
Permanent Ineff=
       F       F
Bank Sta=224.8,260.6
XS Rating Curve= 0 ,0
Exp/Cntr=0.5,0.3

Type RM Length L Ch R = 1 ,1300    ,359.4,375.9,391.3
XS GIS Cut Line= 3
     2181304.895      236098.071     2181716.353      235574.633
     2182069.666      235502.968
#Sta/Elev= 30
       0 1995.43    19.7 1994.11    42.6 1981.81      59 1969.37    88.6 1943.72
   118.1 1913.56   124.6 1907.71   131.2 1903.88   200.1 1905.16   239.4 1902.73
   262.4 1903.09   282.1 1900.62   311.6 1899.41   321.4 1901.79     328 1904.49
   367.3 1905.92   587.1 1907.88   596.9 1910.82   613.3 1921.75   623.2 1925.86
   665.8 1928.05   695.3 1926.19     751 1917.29   783.8 1914.07   849.3 1914.73
   885.4 1917.09   908.3 1915.73   931.3 1916.46   993.5 1934.67  1026.3 1951.26
#Mann= 5 ,-1 , 0
       0      .1       0   282.1    .045       0   321.4      .1       0
     450    .035       0   865.8      .1       0
Bank Sta=282.1,321.4
XS Rating Curve= 0 ,0
Exp/Cntr=0.3,0.1

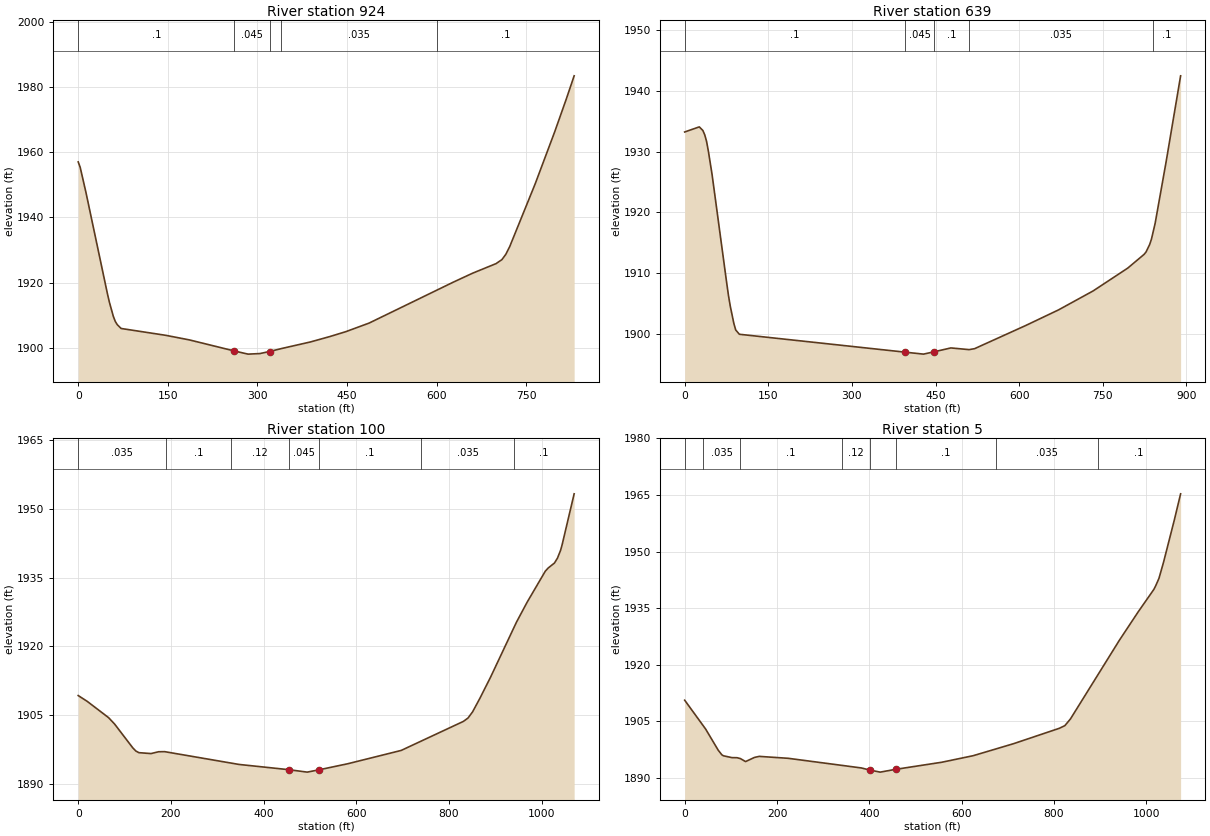
Type RM Length L Ch R = 1 ,924     ,123.3,123.9,121.6
XS GIS Cut Line= 2
     2181466.368      236249.062     2182237.201      235940.034
#Sta/Elev= 30
       0 1956.98     3.3 1955.34    13.1 1947.52      49 1916.52    52.3 1913.93
    58.8 1909.65    62.1 1908.09    65.4  1907.1    71.9 1905.93   147.1 1903.82
   186.4 1902.42   261.6 1899.03   284.4 1898.07   304.1 1898.24   320.4 1898.87
     340 1899.76   389.1 1901.81   421.8 1903.48   447.9 1904.94   487.2 1907.59
   627.8  1920.1   660.4 1922.87   699.7 1925.81   709.5 1927.03     716 1928.64
   722.6 1931.03   765.1  1950.2   797.8 1966.14   817.4 1976.29   830.5 1983.37
#Mann= 5 ,-1 , 0
       0      .1       0   261.6    .045       0   320.4      .1       0
     340    .035       0     600      .1       0
Bank Sta=261.6,320.4
XS Rating Curve= 0 ,0
Exp/Cntr=0.3,0.1

Type RM Length L Ch R = 1 ,639     ,530.1,539.1,521.6
XS GIS Cut Line= 2
     2181531.038      236555.051     2182312.288      236129.704
#Sta/Elev= 30
       0 1933.26    26.2  1934.1    32.7  1933.5      36 1932.78    39.2 1931.74
    42.5  1930.1    49.1 1926.28    75.2 1908.51    78.5 1906.36    81.8 1904.56
    88.3 1901.68    91.6 1900.64    98.1 1899.94   395.7 1896.99   428.4 1896.67
     448 1897.07   477.5 1897.69   510.2 1897.41     520 1897.57   611.6 1901.38
   670.4 1903.95   732.6 1907.08   794.7 1910.84   824.1 1913.11   827.4 1913.48
   833.9 1914.71   837.2 1915.61   843.8 1918.21   863.4  1928.3   889.5 1942.51
#Mann= 5 ,-1 , 0
       0      .1       0   395.7    .045       0     448      .1       0
     510    .035       0     840      .1       0
Bank Sta=395.7,448
XS Rating Curve= 0 ,0
Exp/Cntr=0.3,0.1

Type RM Length L Ch R = 1 ,100     ,88,95.2,89.2
XS GIS Cut Line= 3
     2181611.333      236956.093     2182258.635      236640.772
     2182547.697      236442.855
#Sta/Elev= 30
       0 1909.26    19.6 1907.98    65.5 1904.44    78.6 1903.03   117.8 1897.84
   124.4 1897.15   130.9 1896.79   157.1 1896.59   173.5 1896.99   186.6 1897.01
   346.9 1894.22   454.9 1893.07   494.2 1892.54   520.4 1893.06   582.6 1894.39
   697.1 1897.28   831.3 1903.62   841.2 1904.35     851 1905.68   867.4 1908.76
   890.3 1913.36   945.9  1925.3   968.8 1929.64  1008.1 1936.43  1014.7 1937.15
  1027.8  1938.2  1034.3 1939.27  1040.9 1940.94  1044.2 1942.13  1070.3 1953.31
#Mann= 7 ,-1 , 0
       0    .035       0     190      .1       0     330     .12       0
   454.9    .045       0   520.4      .1       0  740.02    .035       0
  940.02      .1       0
Bank Sta=454.9,520.4
XS Rating Curve= 0 ,0
Exp/Cntr=0.3,0.1

Type RM Length L Ch R = 1 ,5       ,,,
XS GIS Cut Line= 3
2181677.28781272237028.4936545732182063.33800539236829.196984711
2182626.38593982236525.374089398
#Sta/Elev= 30
       0 1910.64    45.5 1902.98    72.8 1897.37    80.5 1896.18    83.9 1895.92
   102.3 1895.43   113.4 1895.41   120.8 1895.17   131.9 1894.38   151.1 1895.48
   161.4 1895.76   224.2 1895.25   382.5  1892.7   401.4 1892.13   423.5 1891.59
     457 1892.33   557.1 1894.21   624.9 1895.94   712.1 1899.11   811.4 1903.19
   823.5  1903.9   835.6 1905.67   941.6 1926.51   982.6 1934.08  1016.2 1939.96
  1019.9 1940.84  1027.4 1942.93  1037.2 1947.14  1060.8 1958.451074.248 1965.29
#Mann= 8 ,-1 , 0
       0     .04       0      40    .035       0     120      .1       0
     340     .12       0   401.4    .045       0     457      .1       0
  674.46    .035       0  894.46      .1       0
Bank Sta=401.4,457
XS Rating Curve= 0 ,0
Exp/Cntr(USF)=0,0
Exp/Cntr=0.3,0.1
LCMann Table=0

Chan Stop Cuts=-1
Use User Specified Reach Order=0
Composite Channel Slope=5